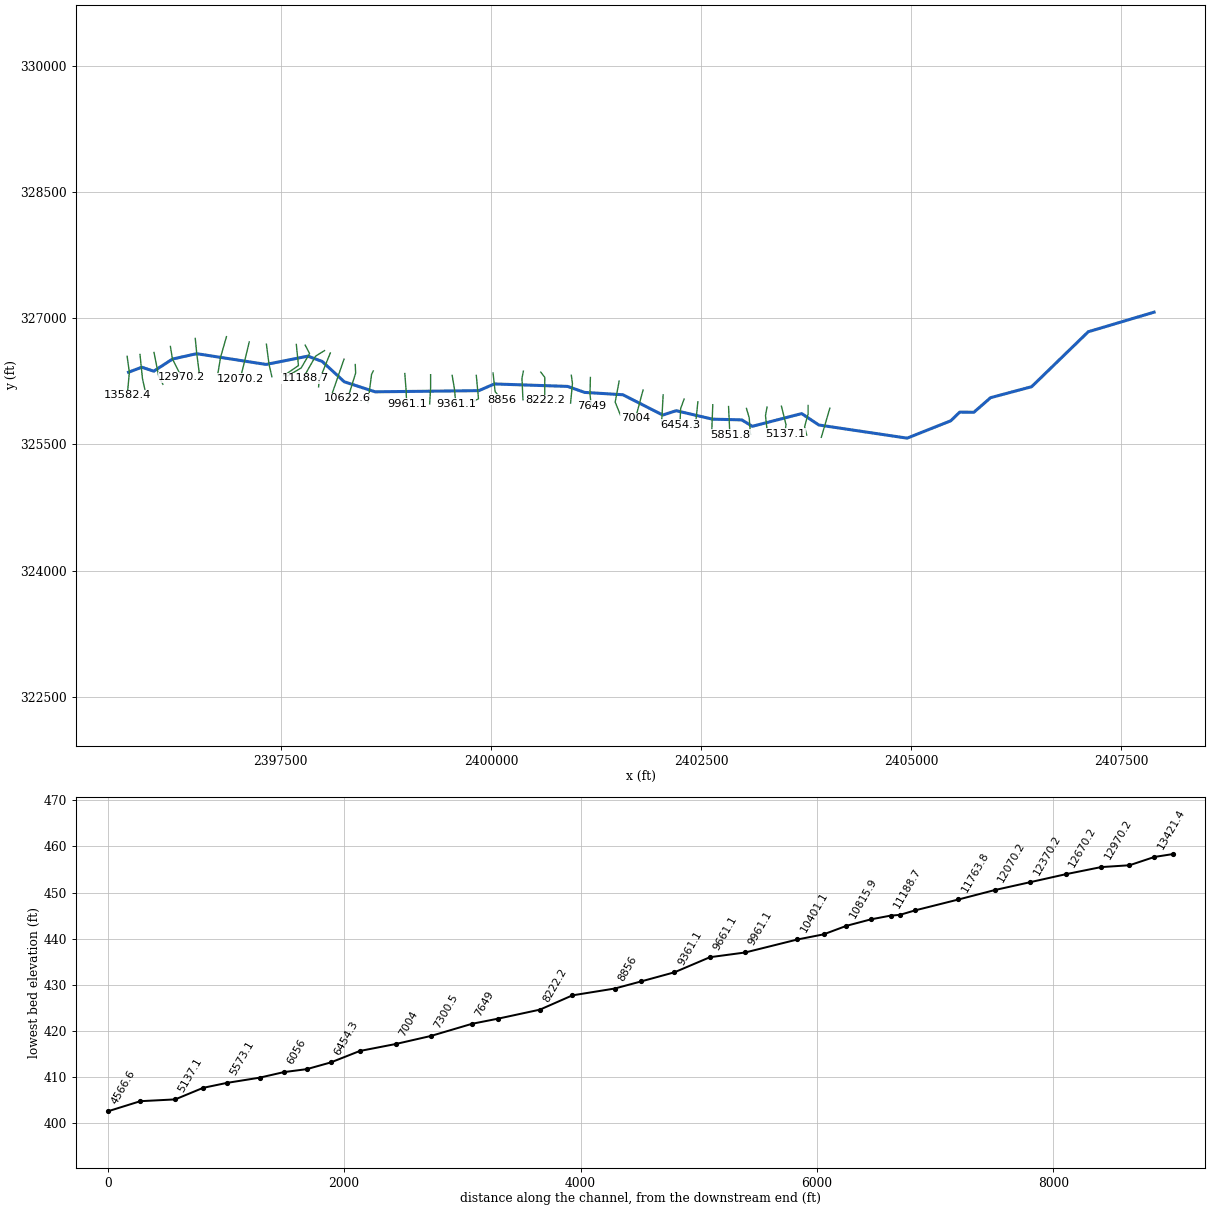
--- BUZZARDRUN.prj (project) ---

Proj Title=BUZZARDRUN
Current Plan=p01
Default Exp/Contr=0,0
English Units
Geom File=g01
Flow File=f01
Plan File=p01
BEGIN DESCRIPTION:
END DESCRIPTION:
DSS Export Rating Curves= 0
DSS Export Rating Curve Sorted= 0
DSS Export Volume Flow Curves= 0
DXF OffsetX= 0
DXF OffsetY= 0
DXF ScaleX= 0
DXF ScaleY= 0

--- BUZZARDRUN.p01 (plan) ---

Plan Title=Floodplain
Program Version=4.00
Geom File=g01
Flow File=f01
K Sum by GR=0
Std Step Tol=0.01
Critical Tol=0.01
Num of Std Step Trials=20
Max Error Tol=0.3
Flow Tol Ratio=0.001
Split Flow NTrial=30
Split Flow Tol=0.02
Split Flow Ratio=0.02
Log Output Level=0
Friction Slope Method=1
Unsteady Friction Slope Method=2
Unsteady Bridges Friction Slope Method=1
Global Log Level=0
CheckData=False
Run HTab=0
Run UNet=0
Run PostProcess=0
UNET Theta=0
UNET Theta Warmup=0
UNET ZTol=0
UNET ZSATol=0
UNET MxIter=0
UNET MaxInSteps=0
UNET DtIC=0
UNET DtMin=0
UNET MaxCRTS=0
UNET WFStab=0
UNET SFStab=0
UNET WFX=0
UNET SFX=0
UNET DSS MLevel=0
UNET DZMax Abort=0
UNET Convert EG Bridges=0
UNET Use Existing IB Tables=0
UNET Froude Limit=0
UNET Froude Power=0
Write IC File=0
Echo Input=False
Echo Output=False
Write Detailed=0

--- BUZZARDRUN.f01 (steady flow) ---

Flow Title=NFF Regression Equation
Program Version=4.00
Number of Profiles=1
Profile Names=P100yr
River Rch & RM=BUZZARDRUN,Main      ,13582.4
837.3944
River Rch & RM=BUZZARDRUN,Main      ,12370.2
914.7933
River Rch & RM=BUZZARDRUN,Main      ,11022.4
959.5967
River Rch & RM=BUZZARDRUN,Main      ,6698.4
1065.041
River Rch & RM=BUZZARDRUN,Main      ,457.4
1182.088
River Rch & RM=BUZZARDRUN,Main      ,172.8
1183.885
Boundary for River Rch & Prof#=BUZZARDRUN,Main      ,1
Up Type=0
Dn Type=3
Dn Slope=0.004585

--- BUZZARDRUN.g01 (geometry) ---

Geom Title=USGS 10m DEM
Program Version=4.10

River Reach=BUZZARDRUN      ,Main
Reach XY= 30
     2395688.401       326357.66     2395846.987      326417.488
     2395988.748      326369.812     2396210.971       326513.91
     2396499.165      326578.146     2397324.529      326450.387
     2397822.082      326548.632     2397992.221      326486.132
     2398255.627      326244.047     2398622.429      326125.021
     2399856.804      326138.909     2400039.744       326218.52
     2400912.359      326189.257     2401115.484      326118.076
     2401570.345      326090.298     2402044.304      325848.979
     2402203.374      325900.727     2402636.318      325800.368
     2402985.276      325791.687     2403110.276      325715.298
     2403697.082       325866.34     2403901.546      325730.831
      2404952.29      325574.673     2405471.387      325781.271
      2405577.29      325883.701     2405745.693      325881.965
     2405945.345      326055.576     2406433.193      326185.785
     2407106.804      326838.562      2407889.79      327071.201

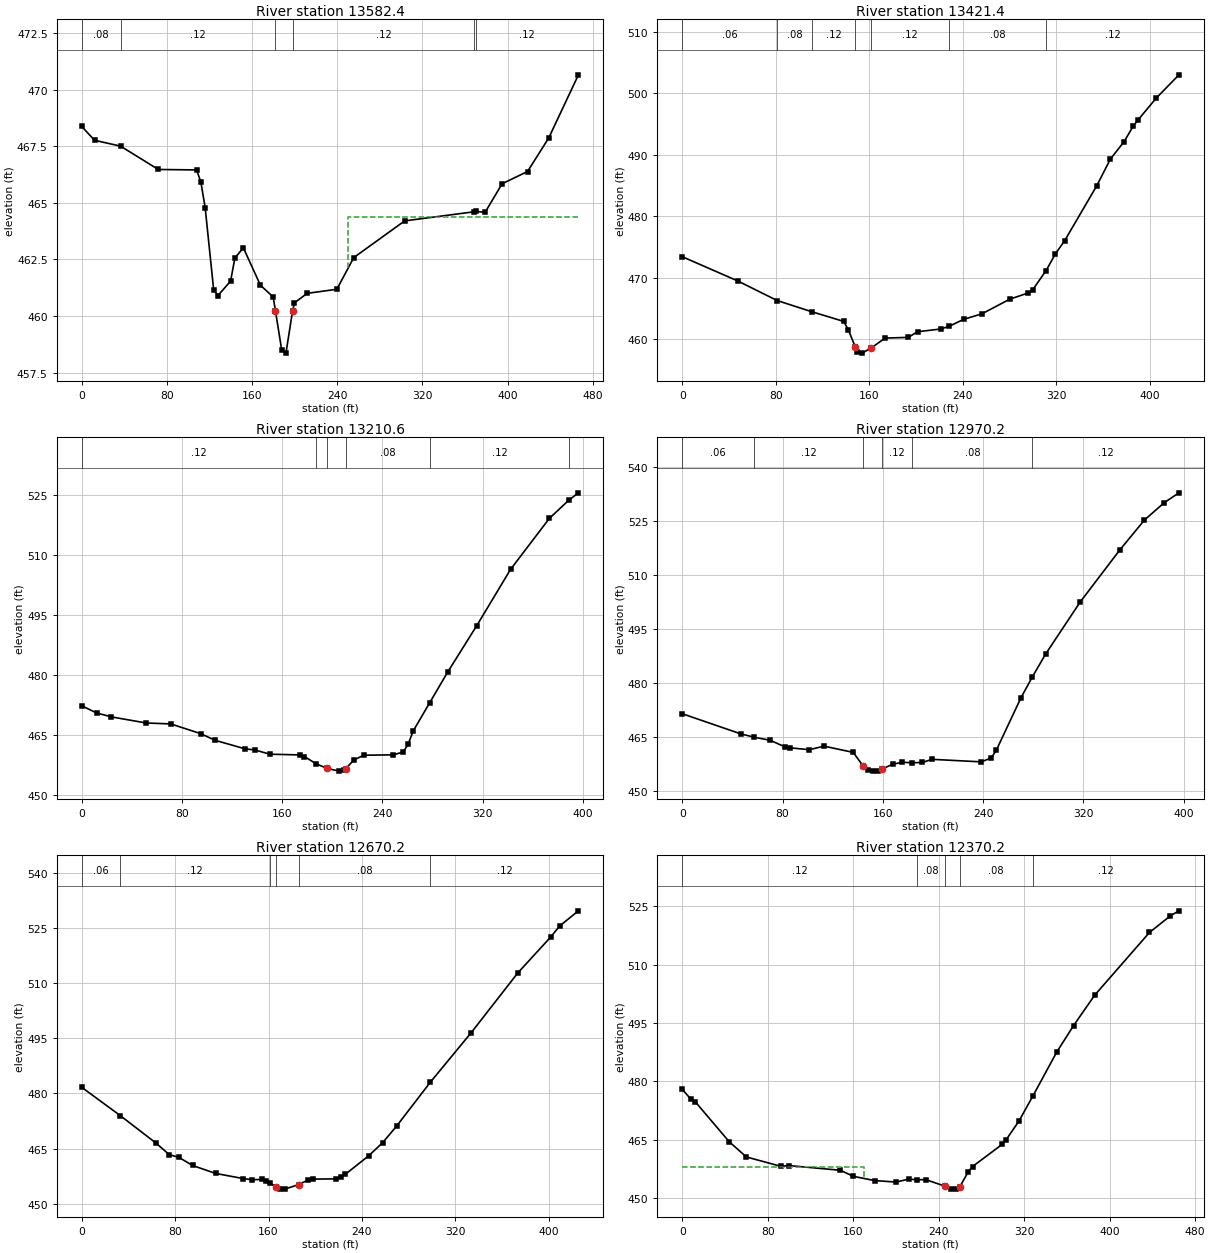
Type RM Length L Ch R = 1 ,13582.4 ,162,161,164.5
XS GIS Cut Line= 3
     2395672.008      326546.718      2395698.36      326356.754
     2395673.488      326083.178
#Sta/Elev= 30
       0  468.37      12  467.76   36.46467.5008    71.9  466.47   107.9  466.45
   111.9  465.91   115.9  464.79   123.9  461.16   127.9   460.9   139.8  461.54
   143.8  462.56   151.8  463.01   167.8  461.36   179.8  460.84  181.97460.2161
   187.8   458.5   191.8  458.36  197.99460.2143   199.8  460.58   211.7     461
   239.6  461.18   255.5  462.58   303.3   464.2  368.78464.6037  370.48464.6168
   378.9  464.58   394.8  465.84   418.7  466.38   438.6  467.86   466.5  470.65
#Mann= 6 ,-1 , 0
       0     .08       0   36.46     .12       0  181.97    .045       0
  197.99     .12       0  368.78     .06       0  370.48     .12       0
#XS Ineff= 2 , 0
                          250.26          464.39
Permanent Ineff=
       F       F
Bank Sta=181.97,197.99
XS Rating Curve= 0 ,0
Exp/Cntr=0.3,0.1

Type RM Length L Ch R = 1 ,13421.4 ,209,210.9,212
XS GIS Cut Line= 3
     2395824.918      326568.705     2395854.474      326282.012
     2395884.052      326148.205
#Sta/Elev= 30
       0   473.4    47.4  469.47   81.25466.2727  110.98464.4476   138.2  462.88
   142.1  461.55  147.94458.7946     150  457.96     154  457.72   161.9  458.58
   173.7  460.17   193.5  460.28   201.4   461.2   221.1  461.64  228.38462.0706
   240.8  463.21   256.6  464.12   280.3  466.49     296   467.5     300  468.02
  311.46471.1505   319.5  473.88   327.4  476.02   354.8  484.93   366.5  489.28
   378.3  492.14   386.1  494.65     390  495.61   405.7  499.19   425.2  502.99
#Mann= 7 ,-1 , 0
       0     .06       0   81.25     .08       0  110.98     .12       0
  147.94    .045       0   161.9     .12       0  228.38     .08       0
  311.46     .12       0
Bank Sta=147.94,161.9
XS Rating Curve= 0 ,0
Exp/Cntr=0.3,0.1

Type RM Length L Ch R = 1 ,13210.6 ,240.6,240.4,246.8
XS GIS Cut Line= 3
     2395991.797      326592.701     2396047.182       326309.79
     2396097.649      326214.168
#Sta/Elev= 30
       0  472.23    11.8  470.46    23.7  469.46    51.3  467.95    71.1   467.7
    94.8   465.3   106.6   463.6   130.3  461.49   138.2  461.21   150.1  460.15
   173.8  459.97   177.7  459.56  187.29457.7154  196.04456.5795   205.4  455.92
   209.3  456.11  210.71 456.533   217.2  458.71   225.1  459.89   248.8  459.99
   256.7  460.72   260.6  462.74   264.6  465.98   277.8473.0515   292.1  480.68
   315.3  492.27   342.3  506.33   373.2  519.03  388.83523.6073   396.4  525.42
#Mann= 6 ,-1 , 0
       0     .12       0  187.29     .08       0  196.04    .045       0
  210.71     .08       0   277.8     .12       0  388.83     .06       0
Bank Sta=196.04,210.71
XS Rating Curve= 0 ,0
Exp/Cntr=0.3,0.1

Type RM Length L Ch R = 1 ,12970.2 ,301.4,300,291.9
XS GIS Cut Line= 3
       2396186.7       326663.97     2396211.466      326513.959
     2396322.013      326296.141
#Sta/Elev= 30
       0  471.44    46.8  465.84   57.26464.9431    70.2  464.07    81.9  462.24
    85.8  461.99   101.4  461.46   113.1  462.45   136.4  460.72   144.5  456.87
   148.1  455.93     152  455.52     156  455.56   159.5   456.1   167.8  457.43
   175.7  457.98  183.66457.8378   191.4  457.92   199.3  458.79   238.7  458.09
   246.6  459.21   250.5  461.26   270.2  475.83   279.2  481.59   289.9  487.98
   317.5  502.43     349  516.82   368.7  525.15   384.5  529.97   396.3  532.72
#Mann= 6 ,-1 , 0
       0     .06       0   57.26     .12       0   144.5    .045       0
   159.5     .12       0  183.66     .08       0   279.2     .12       0
Bank Sta=144.5,159.5
XS Rating Curve= 0 ,0
Exp/Cntr=0.3,0.1

Type RM Length L Ch R = 1 ,12670.2 ,308.5,300,293.3
XS GIS Cut Line= 3
     2396482.527      326759.142     2396500.348      326578.197
     2396531.676      326336.499
#Sta/Elev= 30
       0  481.67      33 473.976    63.2   466.6    75.1  463.32      83  462.66
    94.9  460.41   114.6  458.25   138.3  456.84   146.2  456.53   154.2  456.61
   158.1  456.31  161.55  455.62     166  454.58     170  454.05   173.9  453.97
   185.8  455.21   193.8  456.43   197.8  456.69   217.8  456.76   221.8  457.16
   225.8     458   245.8  463.04   257.7  466.58   269.7  471.11  298.65483.0725
   333.6  496.52   373.6  512.81   401.6  522.52   409.6  525.62   425.5   529.7
#Mann= 6 ,-1 , 0
       0     .06       0      33     .12       0  161.55     .08       0
     166    .045       0   185.8     .08       0  298.65     .12       0
Bank Sta=166,185.8
XS Rating Curve= 0 ,0
Exp/Cntr=0.3,0.1

Type RM Length L Ch R = 1 ,12370.2 ,299.4,300,297.7
XS GIS Cut Line= 3
     2396853.776      326780.477      2396783.37      326534.405
     2396749.338      326328.274
#Sta/Elev= 30
       0  477.89       8   475.4      12  474.76      44  464.42      60  460.52
      92  458.14     100   458.3     148   457.1     160  455.55     180  454.45
     200  454.07     212  454.82  219.78454.6649     228  454.69  246.14452.9773
     252  452.25     256  452.26   259.9   452.9   267.8  456.76   271.7  458.06
   299.3  463.73   303.2  464.97   315.1  469.73  327.98476.0917   350.6  487.53
   366.3  494.31     386  502.11   437.3  518.24     457  522.55   464.9  523.81
#Mann= 5 ,-1 , 0
       0     .12       0  219.78     .08       0  246.14    .045       0
   259.9     .08       0  327.98     .12       0
#XS Ineff= 2 , 0
          169.76  457.84
Permanent Ineff=
       F       F
Bank Sta=246.14,259.9
XS Rating Curve= 0 ,0
Exp/Cntr=0.3,0.1

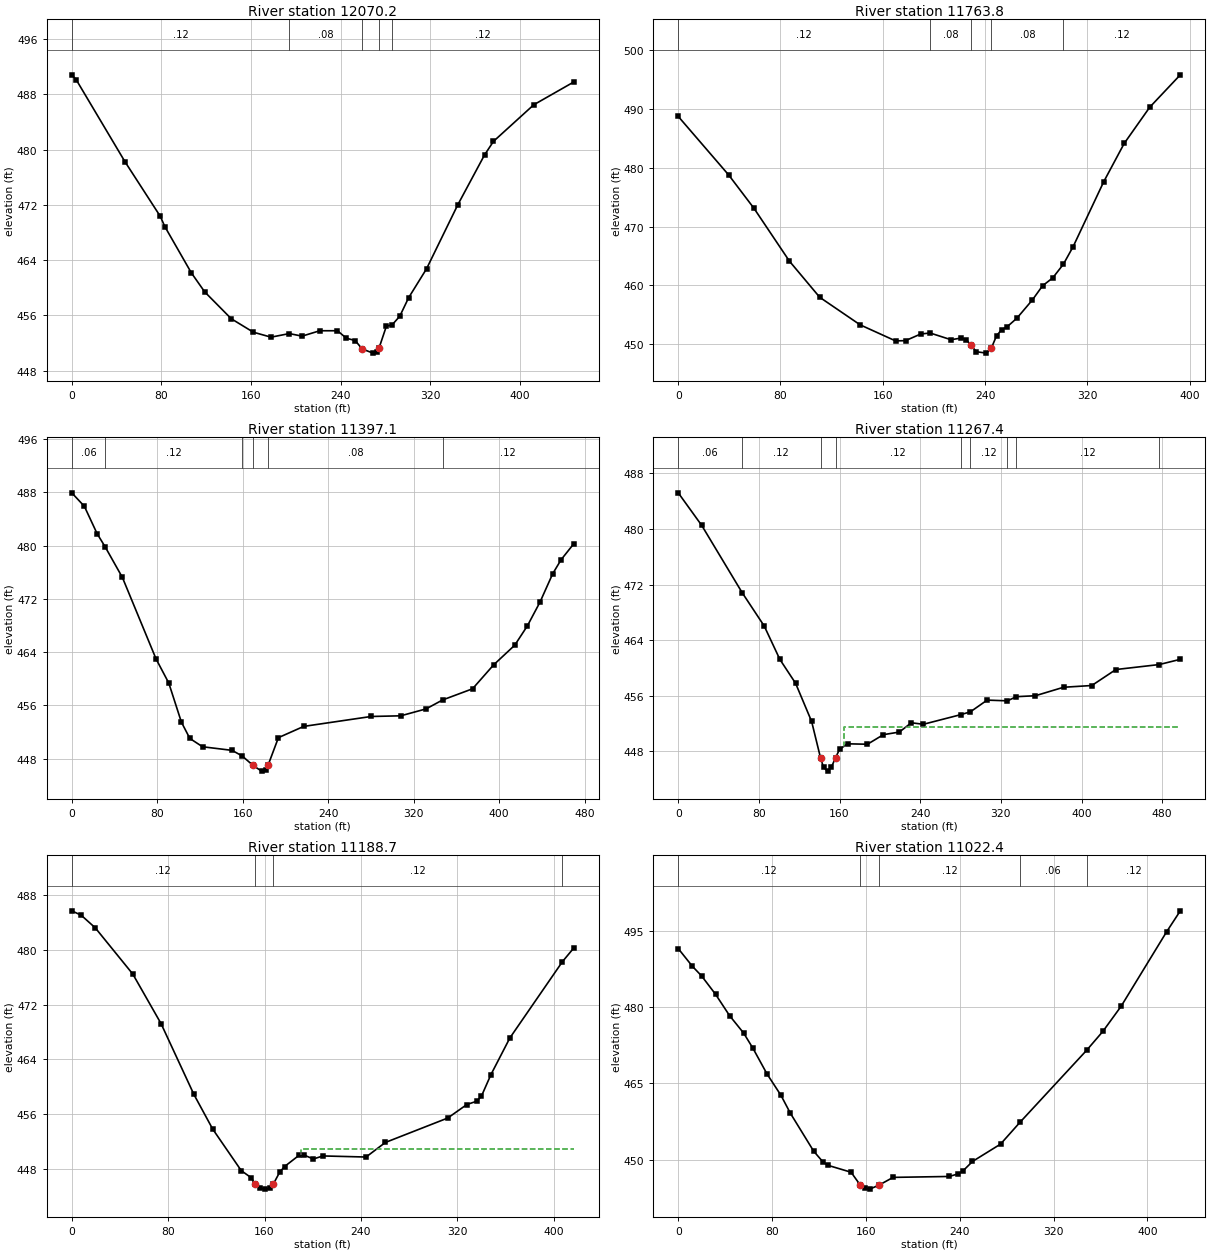
Type RM Length L Ch R = 1 ,12070.2 ,298.4,306.4,315.3
XS GIS Cut Line= 3
     2397124.553      326717.095     2397063.413      326463.559
     2397018.011      326281.951
#Sta/Elev= 30
       0  490.83       4  490.11    47.4  478.27      79  470.34      83  468.87
   106.7  462.16   118.6  459.41   142.3  455.52     162  453.57   177.8  452.85
   194.1  453.37   205.5     453   221.3  453.78   237.1  453.78     245   452.7
   252.9  452.36  259.08  451.15   268.8  450.54   272.8  450.71  274.09  451.23
   280.7  454.43  285.98 454.654   292.7  455.89   300.6  458.57   316.6  462.76
   344.4     472   368.3  479.23   376.3   481.2   412.2  486.49     448   489.8
#Mann= 5 ,-1 , 0
       0     .12       0   194.1     .08       0  259.08    .045       0
  274.09     .08       0  285.98     .12       0
Bank Sta=259.08,274.09
XS Rating Curve= 0 ,0
Exp/Cntr=0.3,0.1

Type RM Length L Ch R = 1 ,11763.8 ,367.2,366.7,364.2
XS GIS Cut Line= 3
     2397328.895      326691.181     2397360.614      326448.204
     2397394.178      326304.258
#Sta/Elev= 30
       0  488.73    39.5  478.77    59.3   473.1      87  464.13   110.7  457.99
   142.3  453.31     170  450.58   177.8  450.62   189.7  451.75  197.05451.9199
   213.4  450.78   221.3  451.06   225.3  450.81   229.2   449.8   233.2  448.74
   241.1   448.5     245  449.37     249  451.43     253   452.5     257  452.92
     265  454.45     277  457.52     285  459.94     293  461.29  301.32463.6076
     309  466.62   332.9  477.64   348.9  484.14   368.9   490.3   392.8   495.8
#Mann= 5 ,-1 , 0
       0     .12       0  197.05     .08       0   229.2    .045       0
     245     .08       0  301.32     .12       0
Bank Sta=229.2,245
XS Rating Curve= 0 ,0
Exp/Cntr=0.3,0.1

Type RM Length L Ch R = 1 ,11397.1 ,143.7,129.7,114.9
XS GIS Cut Line= 3
     2397684.803      326688.045     2397710.165       326436.73
      2397530.97      326313.802
#Sta/Elev= 30
       0  487.95    11.8  485.92    23.7  481.82   31.41 479.788    47.4  475.23
    78.9  462.99    90.8  459.37   102.6   453.5   110.5  451.05   122.4   449.8
     150  449.26   159.5 448.419   169.7  446.99   177.6  446.14   181.6  446.35
  183.75447.0385   193.4  451.17   217.1  452.86   280.2  454.35   307.9  454.45
   331.6  455.49  347.11456.8351   375.1  458.51   394.8   462.1   414.6  465.06
   426.4  467.96   438.3  471.56   450.1  475.79     458  477.91   469.9  480.31
#Mann= 6 ,-1 , 0
       0     .06       0   31.41     .12       0   159.5     .08       0
   169.7    .045       0  183.75     .08       0  347.11     .12       0
Bank Sta=169.7,183.75
XS Rating Curve= 0 ,0
Exp/Cntr=0.3,0.1

Type RM Length L Ch R = 1 ,11267.4 ,78.6,78.7,79.7
XS GIS Cut Line= 4
      2397790.49      326679.434     2397842.527      326579.726
     2397742.717      326408.865     2397581.416      326312.957
#Sta/Elev= 30
       0  485.21    23.3  480.52    63.4470.8426    85.3  466.04   100.8  461.24
   116.4   457.8   132.3  452.31  141.13447.0733   144.1   445.7   148.1  445.16
     152  445.76     156  447.08     160  448.29   167.9  449.09   187.7  449.03
   203.5  450.41   219.3  450.78   231.2  452.12   243.1   451.9  280.51453.2975
  289.81453.6963   306.4  455.38  326.51455.2758  335.42455.8756   354.3  456.01
   382.2  457.23   410.2  457.48   434.1  459.78  477.08460.4969     498  461.25
#Mann= 9 ,-1 , 0
       0     .06       0    63.4     .12       0  141.13    .045       0
     156     .12       0  280.51     .08       0  289.81     .12       0
  326.51     .08       0  335.42     .12       0  477.08     .06       0
#XS Ineff= 2 , 0
                          164.09          451.49
Permanent Ineff=
       F       F
Bank Sta=141.13,156
XS Rating Curve= 0 ,0
Exp/Cntr=0.3,0.1

Type RM Length L Ch R = 1 ,11188.7 ,163.4,166.3,169
XS GIS Cut Line= 4
     2398020.325      326614.911     2397914.402      326548.997
     2397797.961      326344.699     2397791.284      326288.252
#Sta/Elev= 30
       0  485.75     7.8  485.11    19.5  483.26    50.7  476.48    74.1  469.24
   101.4  458.86     117  453.79   140.7  447.71   148.7   446.7  152.01445.8229
   156.6  445.11   160.6     445   164.6   445.1  167.25445.7159   172.6  447.48
   176.6   448.3   188.5  449.93   192.5  450.02   200.5  449.41   208.5  449.86
   244.3   449.7   260.3  451.83   312.1  455.41     328  457.39     336  457.86
     340  458.58     348  461.78   363.7  467.14  407.37478.3185   416.8  480.32
#Mann= 4 ,-1 , 0
       0     .12       0  152.01    .045       0  167.25     .12       0
  407.37     .06       0
#XS Ineff= 2 , 0
                          189.89           450.9
Permanent Ineff=
       F       F
Bank Sta=152.01,167.25
XS Rating Curve= 0 ,0
Exp/Cntr=0.3,0.1

Type RM Length L Ch R = 1 ,11022.4 ,205.7,206.5,207.5
XS GIS Cut Line= 3
     2398089.174      326585.783     2397957.295      326261.092
     2397949.884      326183.808
#Sta/Elev= 30
       0   491.5      12  488.03    19.9  486.12    31.9  482.48    43.8   478.3
    55.8  474.87    63.7  471.89    75.7  466.84    87.6  462.63    95.6  459.12
   115.5  451.65   123.4  449.54   127.4  448.89   147.4  447.51   155.3  444.95
   159.3  444.34   163.3  444.19   171.2  444.98   183.2   446.5     231  446.68
   238.9   447.2   242.9   447.8   250.9  449.63   274.8  453.04  291.26457.2974
  348.24471.4983   362.1  475.22   377.6  480.14   416.4  494.79   428.1  498.92
#Mann= 5 ,-1 , 0
       0     .12       0   155.3    .045       0   171.2     .12       0
  291.26     .06       0  348.24     .12       0
Bank Sta=155.3,171.2
XS Rating Curve= 0 ,0
Exp/Cntr=0.3,0.1

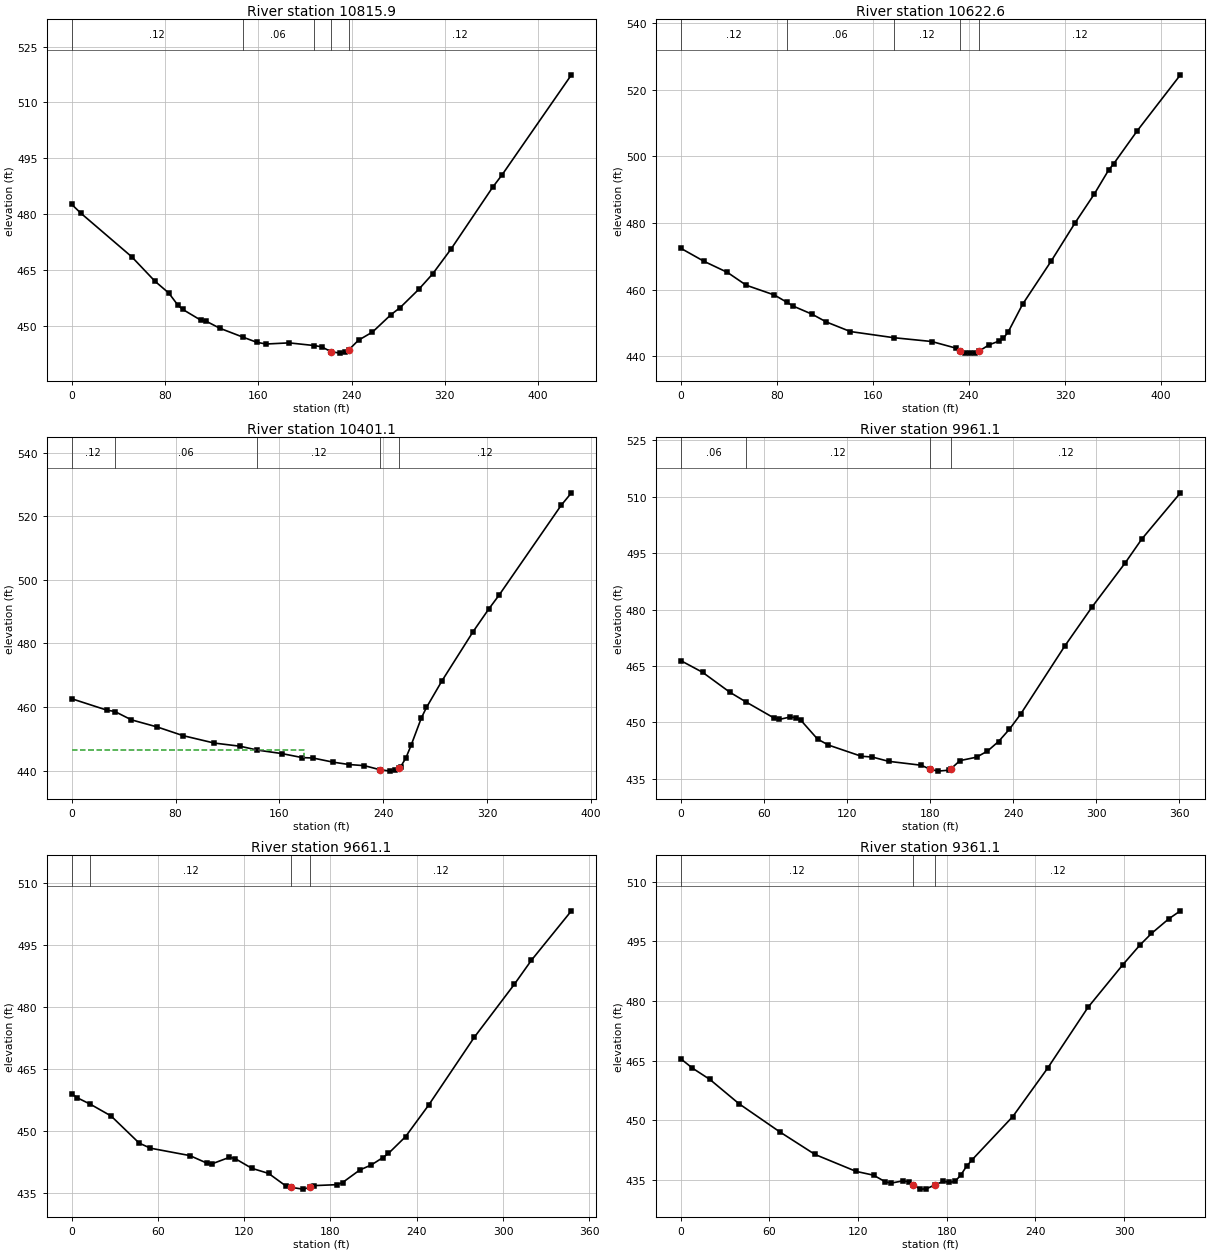
Type RM Length L Ch R = 1 ,10815.9 ,192.3,193.4,193.4
XS GIS Cut Line= 2
      2398252.32      326512.986     2398112.293       326107.91
#Sta/Elev= 30
       0  482.68     7.9  480.31    51.6   468.6    71.4  462.08    83.3   458.9
    91.3  455.57    95.2  454.52   111.1  451.56   115.1  451.39     127  449.47
  146.57447.1177   158.7   445.7   166.7  445.23   186.5  445.54  207.64444.8345
   214.3  444.49   222.6  443.16   230.2  442.79   234.1     443   237.6  443.66
     246  446.26     258  448.44   273.8  453.09   281.8  455.02   297.6  459.87
   309.5     464   325.4  470.72   361.1  487.29   369.1  490.58   428.6  517.41
#Mann= 5 ,-1 , 0
       0     .12       0  146.57     .06       0  207.64     .12       0
   222.6    .045       0   237.6     .12       0
Bank Sta=222.6,237.6
XS Rating Curve= 0 ,0
Exp/Cntr=0.3,0.1

Type RM Length L Ch R = 1 ,10622.6 ,217.2,221.5,225.2
XS GIS Cut Line= 3
     2398386.141      326449.045     2398390.672      326347.681
     2398296.922      326047.333
#Sta/Elev= 30
       0  472.45    19.5   468.5      39  465.17    54.6  461.33      78   458.4
   88.33456.2392    93.7  455.06   109.4  452.63   121.4  450.28   141.3  447.42
   177.5  445.57     209  444.43   228.9  442.47   232.9   441.6   236.9  441.06
   240.9  440.94   244.8  441.05   248.8  441.63   256.8  443.43   264.8  444.52
   268.7  445.42   272.7   447.3   284.7  455.62   308.6  468.64   328.5  480.12
   344.4  488.72   356.4  495.96   360.4  497.74   380.3  507.78   416.1  524.51
#Mann= 5 ,-1 , 0
       0     .12       0   88.33     .06       0   177.5     .12       0
   232.9    .045       0   248.8     .12       0
Bank Sta=232.9,248.8
XS Rating Curve= 0 ,0
Exp/Cntr=0.3,0.1

Type RM Length L Ch R = 1 ,10401.1 ,435.3,440,443.9
XS GIS Cut Line= 3
     2398600.739      326373.123     2398579.908      326332.056
     2398536.932      325995.988
#Sta/Elev= 30
       0  462.61    26.9  459.05   33.29458.5815      46  455.97      66  453.71
    85.9  450.98   109.8  448.66   129.8  447.66  143.01446.4454   161.6  445.37
   177.6  444.08   185.6  443.97   201.5  442.64   213.5  441.91   225.4  441.55
   237.1   440.3   245.3  439.83   249.3  440.07   252.1  440.87   253.3  441.21
   257.3  443.93   261.3   447.9   269.3  456.61   273.2  459.87   285.2  468.29
   309.1  483.72   321.1  490.81     329  495.15   376.9  523.47   384.8   527.4
#Mann= 5 ,-1 , 0
       0     .12       0   33.29     .06       0  143.01     .12       0
   237.1    .045       0   252.1     .12       0
#XS Ineff= 2 , 0
          178.74  446.35
Permanent Ineff=
       F       F
Bank Sta=237.1,252.1
XS Rating Curve= 0 ,0
Exp/Cntr=0.3,0.1

Type RM Length L Ch R = 1 ,9961.1  ,302,300,297.4
XS GIS Cut Line= 3
     2398975.291      326342.315     2398989.667      326161.166
     2398997.958      325982.316
#Sta/Elev= 30
       0  466.43    15.8  463.31    35.6  457.98   47.16 455.424    67.2  451.19
    71.1  450.76      79  451.41      83  451.25    86.9   450.5    98.8  445.55
   106.7  443.95   130.4  440.98   138.3  440.77   150.1  439.63   173.8  438.58
  179.97437.5228   185.7  437.02   193.6  437.27  195.31437.6975   201.6  439.81
   213.6  440.73   221.5  442.35   229.5   444.9   237.4  448.19   245.4  452.15
   277.2  470.23   297.1  480.73     321  492.44   332.9  498.74   360.8  511.04
#Mann= 4 ,-1 , 0
       0     .06       0   47.16     .12       0  179.97    .045       0
  195.31     .12       0
Bank Sta=179.97,195.31
XS Rating Curve= 0 ,0
Exp/Cntr=0.3,0.1

Type RM Length L Ch R = 1 ,9661.1  ,296.4,300,303.2
XS GIS Cut Line= 3
     2399282.567      326328.511     2399282.567      326171.896
     2399271.113      325981.204
#Sta/Elev= 30
       0  459.08     3.9   458.1   13.08456.5263    27.4   453.7      47  447.12
    54.8   445.9    82.2  444.11      94  442.29    97.9  442.15   109.6  443.67
   113.6   443.4   125.3  441.03     137  439.79   148.8   436.8   152.7  436.43
   160.6  435.99  166.04436.3856   168.6  436.84   184.5  437.07   188.4  437.58
   200.4  440.62   208.4  441.84   216.3  443.59   220.3  444.62   232.2  448.68
   248.2  456.28     280  472.73   307.8  485.52   319.8   491.4   347.6  503.35
#Mann= 4 ,-1 , 0
       0     .06       0   13.08     .12       0   152.7    .045       0
  166.04     .12       0
Bank Sta=152.7,166.04
XS Rating Curve= 0 ,0
Exp/Cntr=0.3,0.1

Type RM Length L Ch R = 1 ,9361.1  ,283.6,282.1,282
XS GIS Cut Line= 3
     2399538.959      326320.435     2399566.507       326156.67
     2399581.943      325985.342
#Sta/Elev= 30
       0   465.5     7.9  463.14    19.8  460.27    39.5  454.17    67.2  447.07
    90.9  441.43   118.6  437.19   130.5  436.22   138.4  434.57   142.3  434.22
   150.2  434.79   154.2  434.58   157.2 433.815   162.1  432.72   166.1  432.77
  171.98433.7835   177.8   434.7   181.7  434.41   185.6  434.64   189.5  436.26
   193.4  438.45   197.3  440.15   224.7  450.96   248.2  463.08   275.5  478.36
     299  489.05   310.7  494.05   318.5  496.96   330.3  500.66   338.1  502.65
#Mann= 3 ,-1 , 0
       0     .12       0   157.2    .045       0  171.98     .12       0
Bank Sta=157.2,171.98
XS Rating Curve= 0 ,0
Exp/Cntr=0.3,0.1

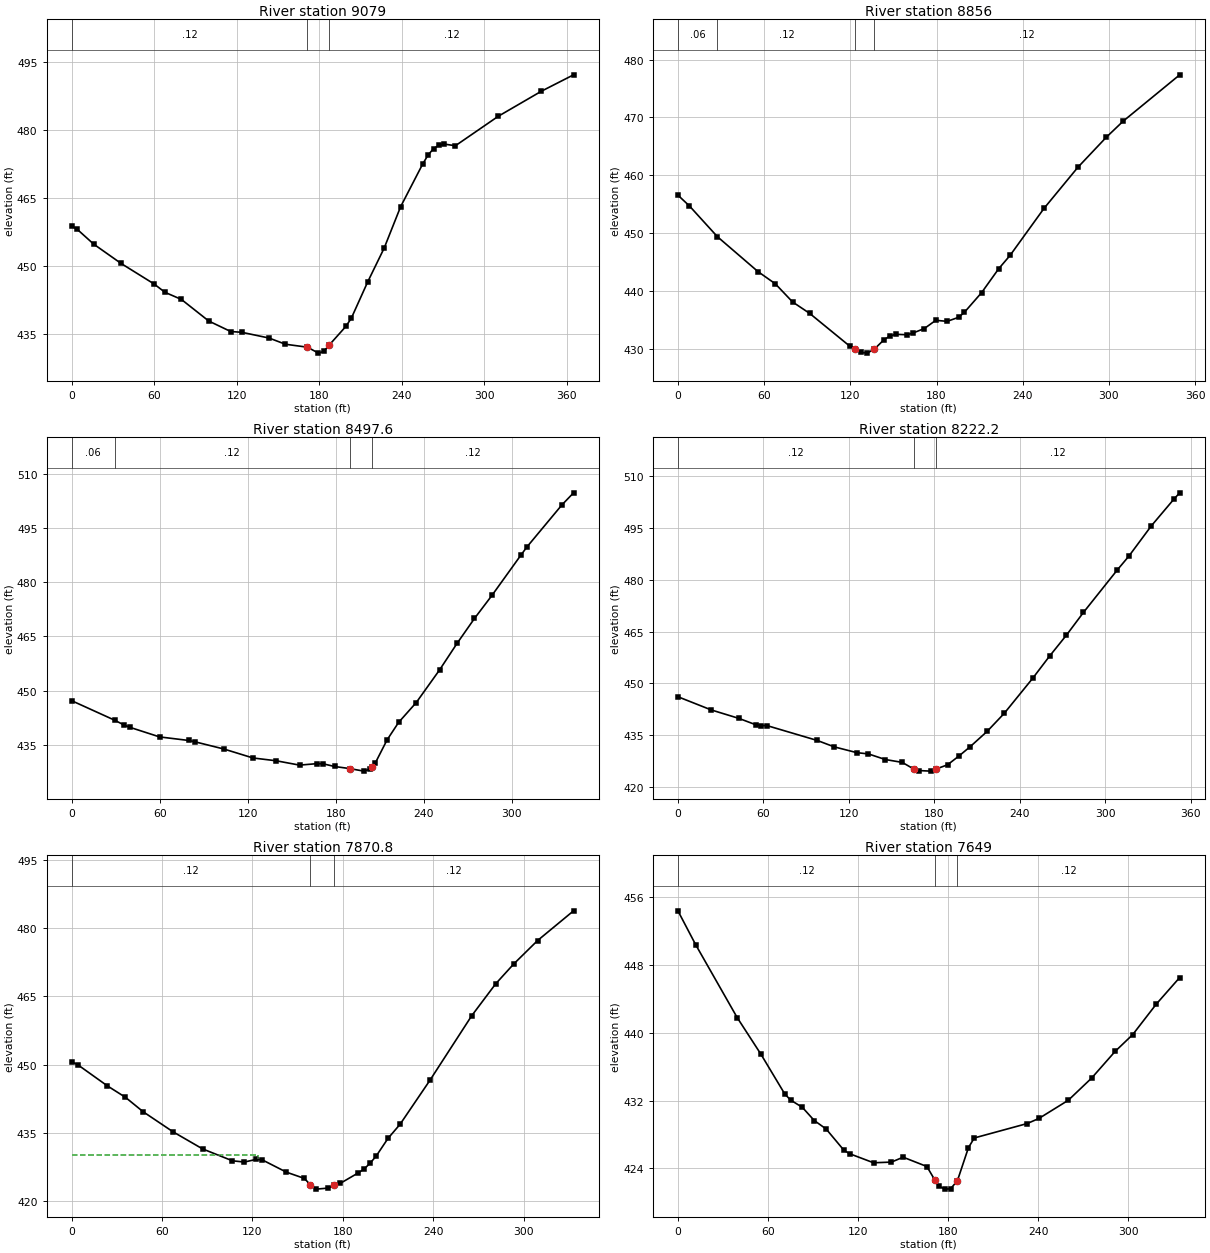
Type RM Length L Ch R = 1 ,9079    ,222.2,223,223.3
XS GIS Cut Line= 3
      2399826.13      326320.483     2399852.043      326042.689
      2399776.42      326001.873
#Sta/Elev= 30
       0  458.76       4  458.06    15.9  454.81    35.9  450.53    59.8  446.02
    67.8  444.16    79.7   442.6    99.6  437.83   115.6  435.51   123.6  435.34
   143.5  434.07   155.4   432.7   171.4  432.05   179.4  430.74   183.3  431.12
   187.3  432.55   199.3  436.63   203.3  438.45   215.2  446.46   227.2  453.94
   239.1  463.03   255.1  472.43   259.1  474.47   263.1  475.88     267  476.63
     271  476.87     279  476.52   310.2  483.03   341.5  488.55   364.9  492.17
#Mann= 3 ,-1 , 0
       0     .12       0   171.4    .045       0   187.3     .12       0
Bank Sta=171.4,187.3
XS Rating Curve= 0 ,0
Exp/Cntr=0.3,0.1

Type RM Length L Ch R = 1 ,8856    ,359.8,358.4,356.6
XS GIS Cut Line= 3
     2400025.458      326348.706      2400049.96      326126.717
     2400132.704      326031.729
#Sta/Elev= 30
       0  456.54       8  454.68   27.51449.3475    55.8   443.3    67.8   441.2
    79.8  438.06    91.7  436.08   119.6  430.41   123.6429.8371   127.6  429.32
   131.6   429.2  136.49429.8379   143.6  431.55   147.6  432.15   151.6  432.46
   159.5  432.38   163.5  432.67   171.5  433.45   179.5  434.88   187.4   434.7
   195.4   435.4   199.4  436.26   211.4  439.67   223.3  443.81   231.2  446.11
   254.8  454.24   278.4  461.36   298.1  466.54   309.9  469.34   349.3  477.37
#Mann= 4 ,-1 , 0
       0     .06       0   27.51     .12       0   123.6    .045       0
  136.49     .12       0
Bank Sta=123.6,136.49
XS Rating Curve= 0 ,0
Exp/Cntr=0.3,0.1

Type RM Length L Ch R = 1 ,8497.6  ,276.3,275.4,274.4
XS GIS Cut Line= 3
     2400386.065      326370.622     2400369.404      326284.356
      2400381.21      326030.189
#Sta/Elev= 30
       0  447.18   29.27441.7965    35.9  440.42    39.9   439.8    59.9  437.18
    79.9  436.19    83.9  435.84   103.8  433.83   123.6  431.36   139.5  430.58
   155.4  429.38   167.4  429.79   171.4  429.75   179.3     429   189.5  428.43
   199.2  427.72   203.2  428.23   204.5  428.82   207.1     430   215.1  436.36
     223  441.21     235  446.68   250.9   455.7   262.8  463.02   274.7  469.92
   286.6  476.28   306.5   487.5   310.5   489.7   334.4  501.34   342.3  504.66
#Mann= 4 ,-1 , 0
       0     .06       0   29.27     .12       0   189.5    .045       0
   204.5     .12       0
Bank Sta=189.5,204.5
XS Rating Curve= 0 ,0
Exp/Cntr=0.3,0.1

Type RM Length L Ch R = 1 ,8222.2  ,351.2,351.4,350.1
XS GIS Cut Line= 3
      2400593.22      326358.564     2400640.932      326296.856
     2400640.238       326022.55
#Sta/Elev= 30
       0  446.16    23.4  442.34    42.9  439.88    54.6  438.06    58.5   437.8
    62.4  437.82    97.9  433.49   109.8  431.64   125.7  429.96   133.7  429.61
   145.6  427.98   157.5  427.15   165.5  425.25   169.4  424.78   177.4  424.62
   181.4  425.26   189.3  426.45   197.3     429   205.2   431.7   217.1  436.13
   229.1  441.35     249  451.46   260.9  457.91   272.8  464.01   284.7  470.57
   308.6  482.94   316.5  486.82   332.4  495.66   348.3  503.42   352.3  505.21
#Mann= 3 ,-1 , 0
       0     .12       0   165.5    .045       0   181.4     .12       0
Bank Sta=165.5,181.4
XS Rating Curve= 0 ,0
Exp/Cntr=0.3,0.1

Type RM Length L Ch R = 1 ,7870.8  ,221.3,221.8,223.8
XS GIS Cut Line= 3
     2400956.714      326321.813     2400970.099      326223.939
     2400947.876      325990.606
#Sta/Elev= 30
       0  450.64       4     450    23.7  445.35    35.6  442.86    47.4  439.68
    67.2  435.28    86.9  431.51   106.7   428.9   114.7  428.63   122.6  429.23
   126.6  429.09   142.5  426.41   154.4  425.04   158.4  423.66   162.4  422.68
   170.3  422.91   174.3  423.55   178.2  423.93   190.2  426.24   194.1  427.09
   198.1  428.38   202.1  429.92     210  433.83     218  436.92   237.8  446.57
   265.6  460.78   281.5  467.78   293.4  472.11   309.3  477.28   333.2  483.81
#Mann= 3 ,-1 , 0
       0     .12       0   158.4    .045       0   174.3     .12       0
#XS Ineff= 2 , 0
          123.53  430.17
Permanent Ineff=
       F       F
Bank Sta=158.4,174.3
XS Rating Curve= 0 ,0
Exp/Cntr=0.3,0.1

Type RM Length L Ch R = 1 ,7649    ,352.1,348.5,343.7
XS GIS Cut Line= 3
     2401183.543      326295.399     2401178.356      326098.029
      2401193.71      325962.134
#Sta/Elev= 30
       0  454.41    11.8  450.42    39.5   441.8    55.3  437.48    71.1  432.81
      75  432.08    82.9  431.21    90.8  429.66    98.7  428.66   110.6  426.14
   114.5  425.73   130.3  424.67   142.2  424.75     150  425.33   165.8  424.23
  171.11 422.635   173.7  421.93   177.7  421.56   181.6   421.6  186.17 422.565
   193.5  426.46   197.4   427.6   232.6   429.3   240.4   429.9     260  432.05
   275.6  434.68   291.2  437.82   302.9   439.8   318.6   443.4   334.2  446.54
#Mann= 3 ,-1 , 0
       0     .12       0  171.11    .045       0  186.17     .12       0
Bank Sta=171.11,186.17
XS Rating Curve= 0 ,0
Exp/Cntr=0.3,0.1

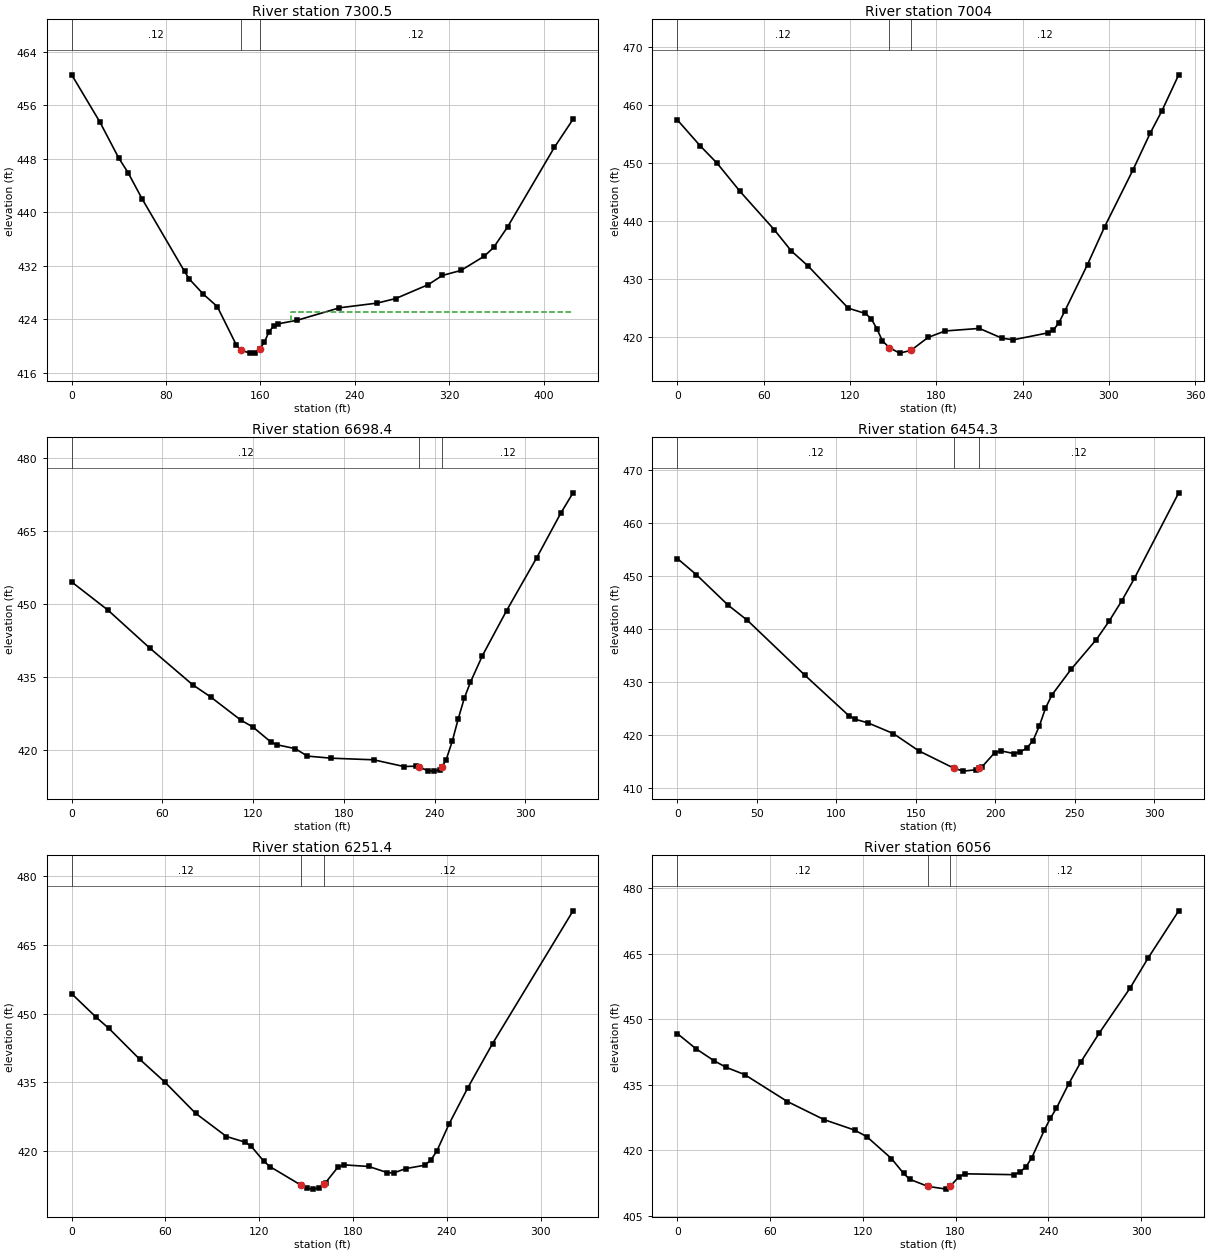
Type RM Length L Ch R = 1 ,7300.5  ,298.1,296.5,294.6
XS GIS Cut Line= 3
     2401525.629      326252.869     2401478.432      326002.411
     2401542.321      325844.773
#Sta/Elev= 30
       0  460.55    23.9  453.48    39.8  448.12    47.8   445.9    59.7  441.98
    95.6  431.15    99.6  430.01   111.5  427.75   123.4  425.88   139.4  420.19
   143.4  419.35   151.3  418.92   155.3  418.97   159.3  419.54   163.3  420.55
   167.3  422.15   171.2  422.96   175.2  423.31   191.2  423.84     227   425.7
   258.8   426.4   274.6  427.08   302.3  429.17   314.2  430.54     330  431.29
   349.8  433.43   357.7  434.73   369.6  437.83   409.1  449.68     425  453.91
#Mann= 3 ,-1 , 0
       0     .12       0   143.4    .045       0   159.3     .12       0
#XS Ineff= 2 , 0
                          185.76           425.1
Permanent Ineff=
       F       F
Bank Sta=143.4,159.3
XS Rating Curve= 0 ,0
Exp/Cntr=0.3,0.1

Type RM Length L Ch R = 1 ,7004    ,300.9,305.6,310.3
XS GIS Cut Line= 2
     2401809.971      326146.161     2401719.925      325809.356
#Sta/Elev= 30
       0  457.47    15.8  453.01    27.7  449.97    43.6  445.11    67.4  438.49
    79.2  434.84    91.1  432.18   118.8  424.95   130.7  424.03   134.7  423.16
   138.7  421.41   142.6  419.28   147.4  418.13   154.5  417.18   162.4  417.65
   174.3  419.89   186.2  421.01     210  421.45   225.8  419.75   233.7  419.49
   257.5  420.67   261.5  421.17   265.4  422.47   269.4  424.45   285.2  432.49
   297.1  439.01   316.9  448.88   328.8  455.19   336.8  458.97   348.6  465.26
#Mann= 3 ,-1 , 0
       0     .12       0   147.4    .045       0   162.4     .12       0
Bank Sta=147.4,162.4
XS Rating Curve= 0 ,0
Exp/Cntr=0.3,0.1

Type RM Length L Ch R = 1 ,6698.4  ,238.1,244.1,245.7
XS GIS Cut Line= 2
     2402049.169      326088.231     2402030.689      325757.273
#Sta/Elev= 30
       0  454.58      24  448.78    51.9   440.9    79.9  433.45    91.8  430.94
   111.8  426.16   119.8  424.74   131.8  421.62   135.8  421.08   147.8  420.29
   155.8  418.75   171.7  418.32   199.7  417.99   219.6  416.61   227.6  416.68
   229.8  416.45   235.6  415.77   239.6  415.66   243.6  415.91   244.8  416.54
   247.6  418.01   251.6  421.79   255.6  426.45   259.6  430.69   263.6  433.93
   271.6  439.45   287.5  448.66   307.5  459.59   323.5  468.81   331.5  472.93
#Mann= 3 ,-1 , 0
       0     .12       0   229.8    .045       0   244.8     .12       0
Bank Sta=229.8,244.8
XS Rating Curve= 0 ,0
Exp/Cntr=0.3,0.1

Type RM Length L Ch R = 1 ,6454.3  ,208,202.9,200.8
XS GIS Cut Line= 3
     2402298.459      326039.177     2402257.251      325926.543
     2402248.571      325731.231
#Sta/Elev= 30
       0  453.28      12  450.22      32  444.47      44  441.64      80  431.34
   107.9  423.64   111.9  422.97   119.9  422.29   135.9  420.27   151.8  417.03
  173.97413.7452   179.8  413.19   187.8  413.44  189.71413.7224   191.8  414.04
   199.7  416.69   203.7     417   211.7  416.51   215.7  416.82   219.7  417.51
   223.7  418.92   227.7  421.68   231.6  425.06   235.6  427.54   247.6  432.36
   263.6  438.01   271.6  441.46   279.5  445.26   287.5  449.52   315.4  465.67
#Mann= 3 ,-1 , 0
       0     .12       0  173.97    .045       0  189.71     .12       0
Bank Sta=173.97,189.71
XS Rating Curve= 0 ,0
Exp/Cntr=0.3,0.1

Type RM Length L Ch R = 1 ,6251.4  ,193.9,195.4,197
XS GIS Cut Line= 2
     2402462.281      326006.941     2402429.126      325687.828
#Sta/Elev= 30
       0  454.34    15.8  449.17    23.8  446.79    43.6  440.03    59.4  435.14
    79.2  428.29      99  423.21   110.9  421.98   114.9  421.05   122.8  417.86
   126.8  416.65   146.6  412.62   150.5  411.87   154.5  411.73   158.4  412.01
  161.22412.7996   162.4  413.13   170.3  416.51   174.3  417.02   190.1  416.67
     202  415.33     206  415.26   213.9  416.22   225.8  416.94   229.7     418
   233.7  420.08   241.6  426.04   253.5  433.87   269.3  443.48   320.8  472.44
#Mann= 3 ,-1 , 0
       0     .12       0   146.6    .045       0  161.22     .12       0
Bank Sta=146.6,161.22
XS Rating Curve= 0 ,0
Exp/Cntr=0.3,0.1

Type RM Length L Ch R = 1 ,6056    ,202.2,204.2,206.1
XS GIS Cut Line= 2
     2402639.607      325972.048     2402627.043      325647.898
#Sta/Elev= 30
       0   446.7    11.9  443.27    23.7  440.49    31.6  438.97    43.5  437.32
    71.2  431.14    94.9     427   114.7   424.6   122.6  423.09   138.5  418.09
   146.4  414.68   150.3  413.34   162.2   411.7   174.1  411.08  176.54411.7432
     182  413.82   185.9  414.59   217.6  414.39   221.5  414.96   225.5  416.14
   229.4  418.32   237.4  424.56   241.3  427.26   245.3  429.63   253.2  435.18
   261.1  440.22     273  446.83   292.8  457.06   304.6     464   324.4  474.82
#Mann= 3 ,-1 , 0
       0     .12       0   162.2    .045       0  176.54     .12       0
Bank Sta=162.2,176.54
XS Rating Curve= 0 ,0
Exp/Cntr=0.3,0.1

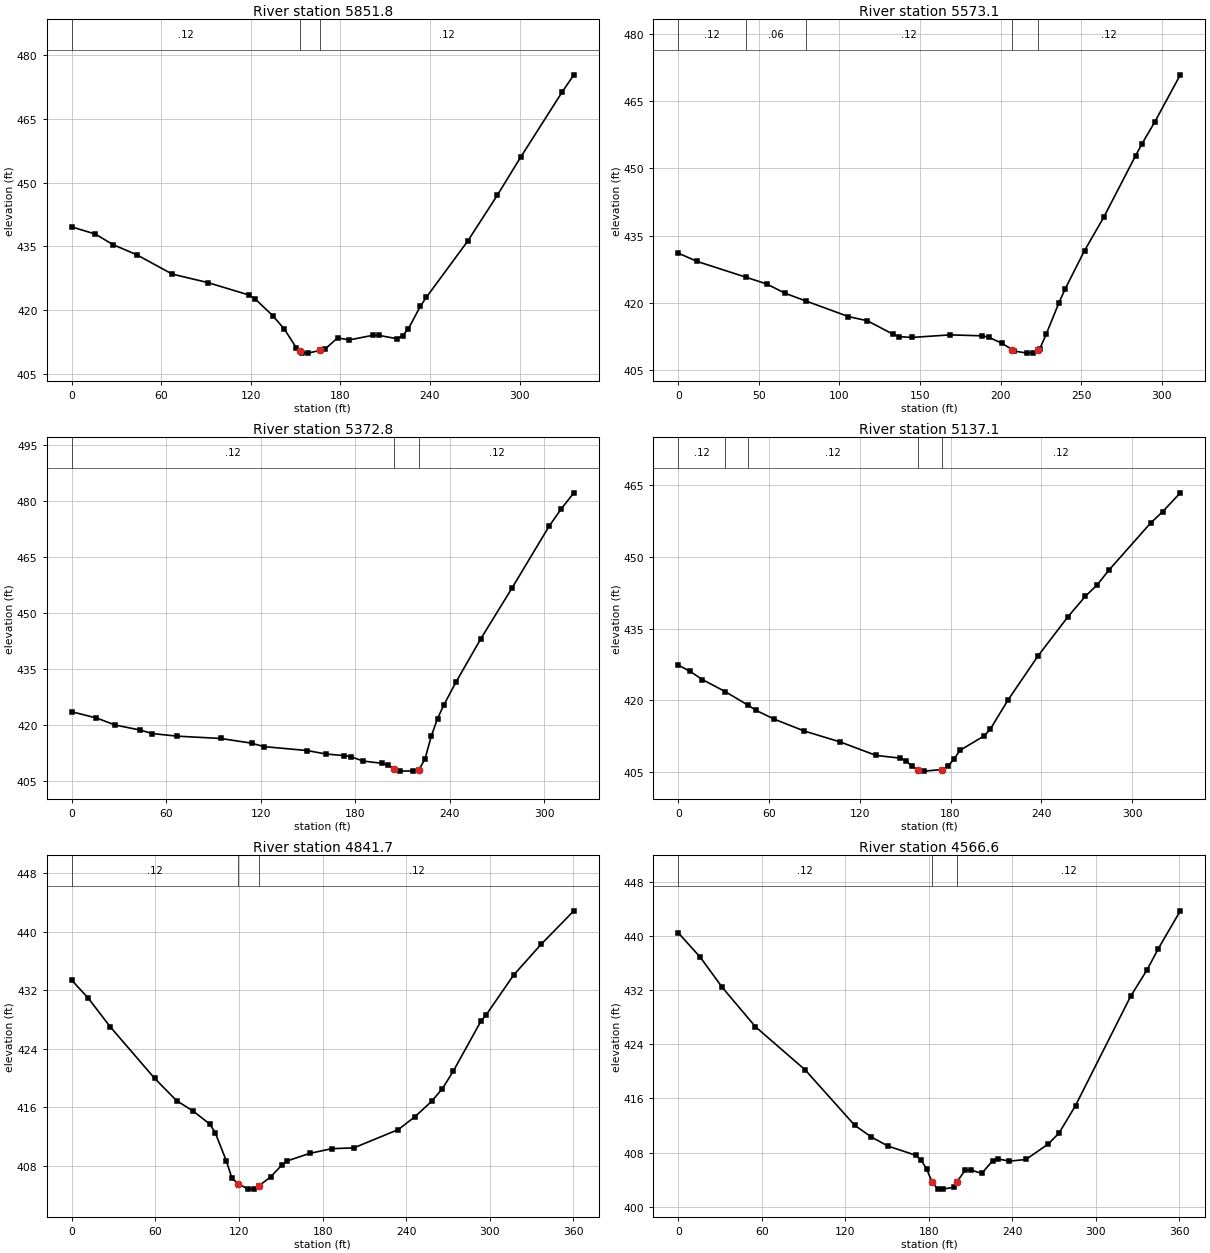
Type RM Length L Ch R = 1 ,5851.8  ,277,278.7,279.6
XS GIS Cut Line= 2
     2402827.266      325950.094     2402843.189      325614.043
#Sta/Elev= 30
       0  439.58    15.8   437.9    27.7   435.4    43.5  433.04    67.3  428.48
      91   426.5   118.7  423.56   122.7  422.68   134.6  418.73   142.5   415.5
   150.4  411.16  152.61410.4804   154.4  409.93   158.3  409.88   166.2  410.51
     170  410.92   178.1  413.47     186  412.99   201.9  414.09   205.8  414.06
   217.7  413.28   221.6  413.94   225.6  415.66   233.5  420.87   237.5  422.99
   265.2   436.2     285  446.98   300.8  456.01   328.5   471.3   336.4  475.38
#Mann= 3 ,-1 , 0
       0     .12       0  152.61    .045       0   166.2     .12       0
Bank Sta=152.61,166.2
XS Rating Curve= 0 ,0
Exp/Cntr=0.3,0.1

Type RM Length L Ch R = 1 ,5573.1  ,200,200.2,201
XS GIS Cut Line= 3
     2403040.293      325928.057     2403073.224      325815.432
     2403087.113      325621.856
#Sta/Elev= 30
       0  431.08    11.7  429.23   42.01425.7015    54.8   424.2    66.5  422.08
   79.47420.3542   105.6   416.9   117.3  415.97   133.2  412.97   137.1  412.41
   145.1  412.25   168.8  412.82   188.6   412.6   192.6  412.28   200.5  410.99
  207.03409.5478   208.4   409.2   216.4  408.74   220.3  408.85  223.28 409.513
   224.3  409.74   228.2  412.96   236.2  420.05   240.1  423.17     252  431.65
   263.9  439.09   283.7  452.88   287.6  455.49   295.6  460.42   311.4  470.92
#Mann= 5 ,-1 , 0
       0     .12       0   42.01     .06       0   79.47     .12       0
  207.03    .045       0  223.28     .12       0
Bank Sta=207.03,223.28
XS Rating Curve= 0 ,0
Exp/Cntr=0.3,0.1

Type RM Length L Ch R = 1 ,5372.8  ,232.8,235.8,238.6
XS GIS Cut Line= 3
      2403284.93      325943.061       2403266.8      325842.342
     2403290.238      325627.064
#Sta/Elev= 30
       0  423.57    15.7   421.9    27.6  420.02    43.3  418.69    51.2  417.73
    66.9  417.04    94.5  416.42   114.2  415.16     122  414.24   149.6  413.18
   161.4  412.26   173.2  411.82   177.2  411.56     185  410.37   196.8  409.78
   200.8  409.31   204.7  408.23   208.6  407.67   216.5  407.74   220.5  408.02
   224.4  410.98   228.3  416.97   232.3  421.75   236.2  425.28   244.1  431.58
   259.8  443.12   279.5  456.63   303.1  473.22     311     478   318.9  482.23
#Mann= 3 ,-1 , 0
       0     .12       0   204.7    .045       0   220.5     .12       0
Bank Sta=204.7,220.5
XS Rating Curve= 0 ,0
Exp/Cntr=0.3,0.1

Type RM Length L Ch R = 1 ,5137.1  ,306.8,295.3,283.3
XS GIS Cut Line= 3
     2403456.507      325954.072     2403510.724      325734.703
     2403496.835      325629.668
#Sta/Elev= 30
       0  427.35     7.9  426.02    15.9  424.33   30.98421.8182   45.79419.0275
    51.5  417.87    63.4  416.05    83.2  413.57     107  411.28   130.8  408.45
   146.7  407.89   150.6  407.31   154.4  406.21   158.6  405.35   162.5  405.17
   174.4   405.5   178.4  406.24   182.4  407.73   186.3  409.53   202.2  412.53
   206.2   413.9     218  420.04   237.7  429.21   257.4  437.37   269.1  441.73
     277  444.15   284.8  447.25   312.3  457.07   320.2  459.43   331.9  463.38
#Mann= 5 ,-1 , 0
       0     .12       0   30.98     .06       0   45.79     .12       0
   158.6    .045       0   174.4     .12       0
Bank Sta=158.6,174.4
XS Rating Curve= 0 ,0
Exp/Cntr=0.3,0.1

Type RM Length L Ch R = 1 ,4841.7  ,276.9,275.2,270.9
XS GIS Cut Line= 4
     2403773.745      325963.002     2403773.745      325864.043
     2403732.078      325710.398     2403757.251      325611.439
#Sta/Elev= 30
       0  433.34    11.9  430.87    27.7  426.95    59.4  419.94    75.2  416.88
    87.1  415.45      99  413.68   102.9  412.52   110.9  408.65   114.9   406.3
   119.6  405.46   126.8  404.78   130.8   404.8   134.6  405.27   142.7  406.45
   150.7  408.06   154.7  408.64   170.6  409.66   186.5  410.31   202.4  410.42
   234.3  412.92   246.2  414.67   258.2  416.78     266  418.52   273.9  420.95
   293.5   427.7   297.4  428.61   317.1  434.05   336.7  438.23   360.3  442.83
#Mann= 3 ,-1 , 0
       0     .12       0   119.6    .045       0   134.6     .12       0
Bank Sta=119.6,134.6
XS Rating Curve= 0 ,0
Exp/Cntr=0.3,0.1

Type RM Length L Ch R = 1 ,4566.6  ,323.8,328,332.4
XS GIS Cut Line= 2
     2404032.425      325930.884     2403930.863       325584.53
#Sta/Elev= 30
       0  440.53    15.9  436.89    31.7  432.43    55.5  426.62    91.2  420.24
   126.9  412.02   138.8   410.3   150.7  408.96   170.6   407.6   174.5  406.89
   178.5  405.59   182.4  403.66   186.4  402.61   190.4  402.58   198.3  402.87
  200.36403.6638   206.2  405.36   210.2  405.42   218.2  404.92   226.1   406.8
     230  407.05     238  406.72   249.9  406.97   265.8  409.23   273.7  410.87
   285.6  414.96   325.2  431.13   337.1  435.08   345.1  438.19   360.9  443.78
#Mann= 3 ,-1 , 0
       0     .12       0   182.4    .045       0  200.36     .12       0
Bank Sta=182.4,200.36
XS Rating Curve= 0 ,0
Exp/Cntr=0.3,0.1