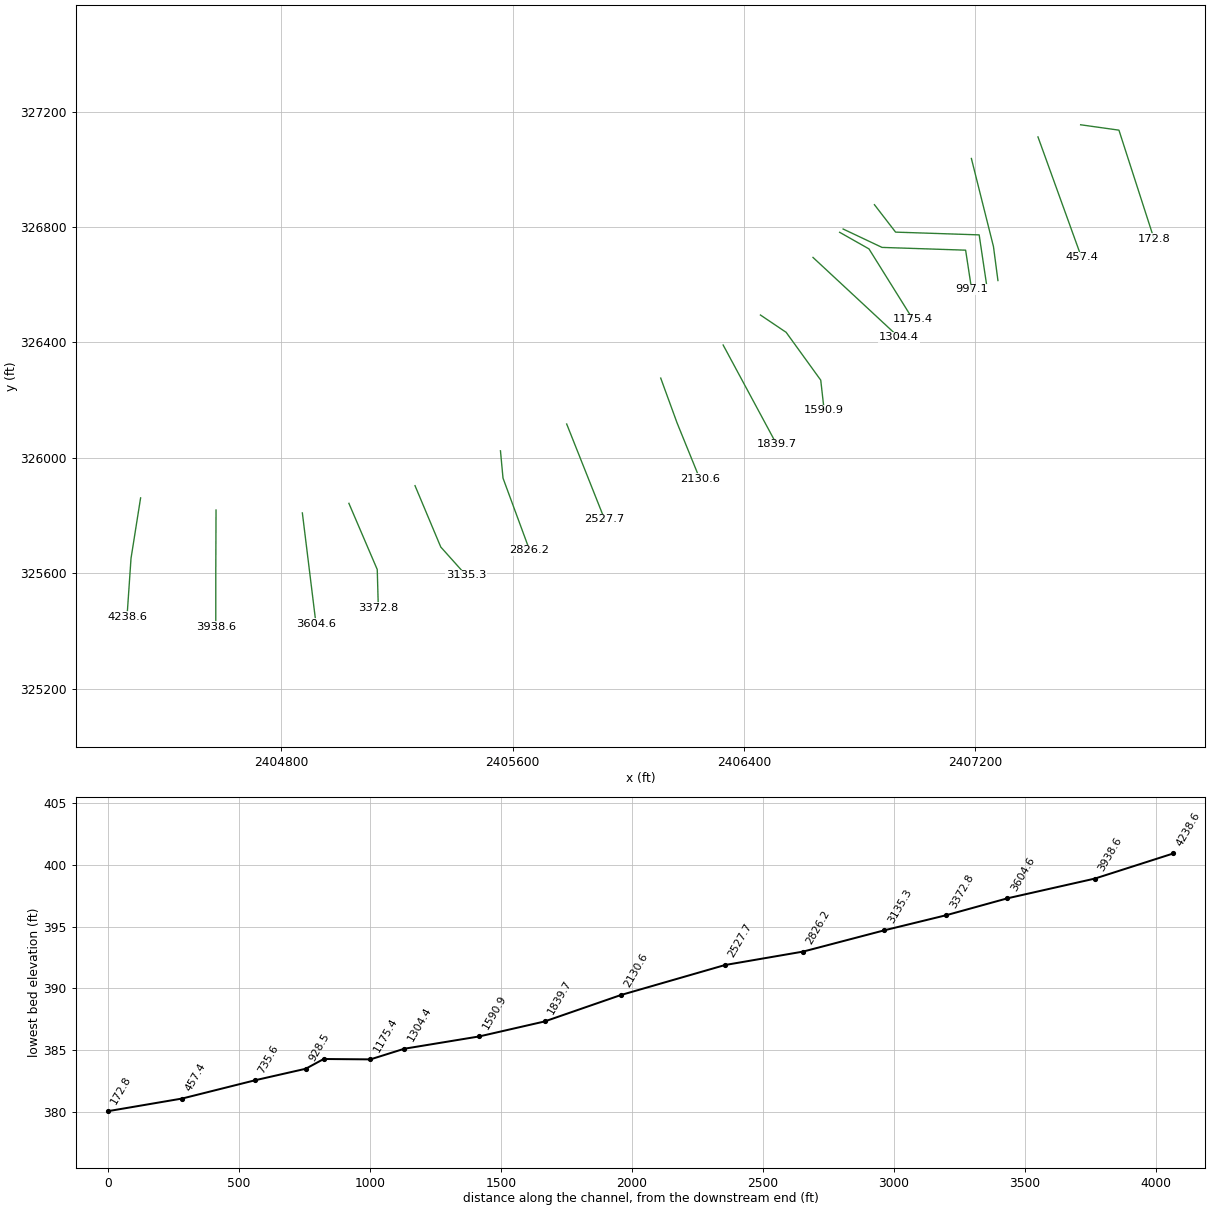
HEC-RAS study BUZZARDRUN.prj: BUZZARDRUN

--- BUZZARDRUN.g01 (geometry) --- (continued)

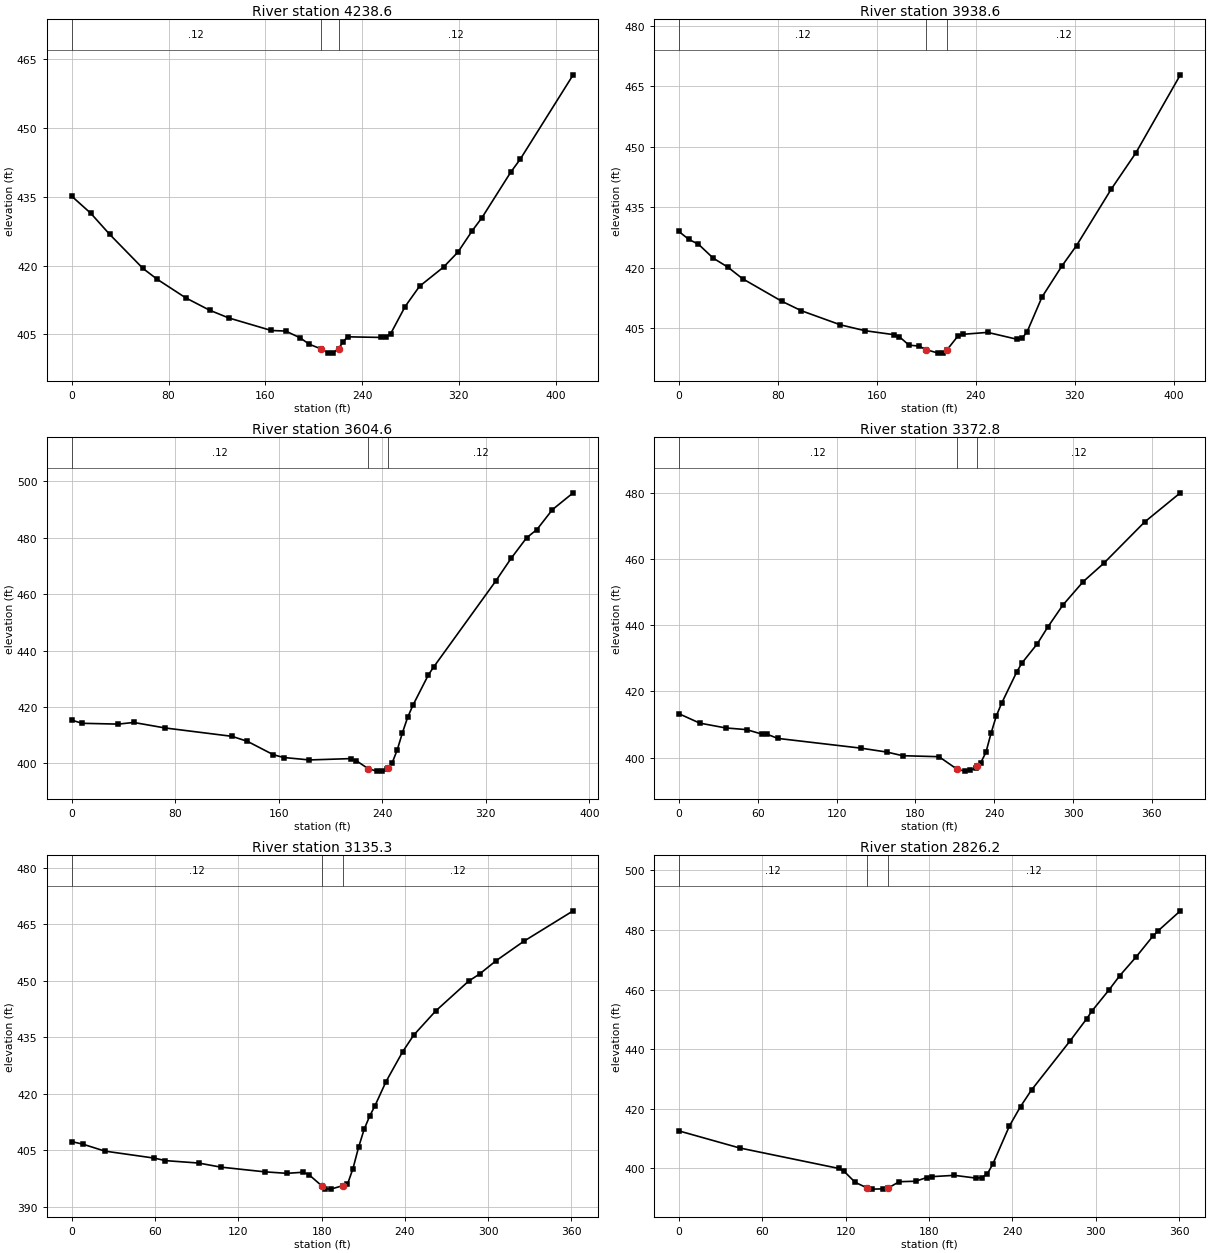
Type RM Length L Ch R = 1 ,4238.6  ,296.4,300,301.5
XS GIS Cut Line= 3
     2404312.988      325861.496      2404279.83      325651.941
     2404265.997      325450.081
#Sta/Elev= 30
       0   435.1    15.7  431.39    31.4  426.78    58.9  419.36    70.7     417
    94.3  412.95   113.9  410.28   129.6   408.6     165  405.85   176.8  405.73
   188.6  404.28   196.4  402.85  205.75 401.879   212.2  400.92   216.1     401
  220.55401.8545   224.1  403.31     228  404.47   255.8  404.34   259.8  404.45
   263.7  405.18   275.6  411.07   287.5  415.48   307.4  419.67   319.3  422.94
   331.2  427.63   339.1  430.42   362.9  440.33   370.9  443.22   414.5  461.54
#Mann= 3 ,-1 , 0
       0     .12       0  205.75    .045       0  220.55     .12       0
Bank Sta=205.75,220.55
XS Rating Curve= 0 ,0
Exp/Cntr=0.3,0.1

Type RM Length L Ch R = 1 ,3938.6  ,331,333.9,336.8
XS GIS Cut Line= 3
     2404573.849      325819.475     2404572.977      325605.923
     2404572.977      325414.307
#Sta/Elev= 30
       0  429.01     7.9  427.07    15.8  425.85    27.7  422.41    39.6  420.17
    51.4  417.32      83  411.75    98.9  409.39   130.5  405.89   150.3  404.44
     174  403.44     178  402.98   185.9  400.86   193.8  400.63  200.04399.7107
   209.6  398.88   213.6  399.02  216.65399.6986   225.5  403.13   229.5  403.54
   249.5  404.02   273.4   402.3   277.4   402.6   281.4  404.18   293.4  412.77
   309.4  420.42   321.3  425.52   349.3  439.48   369.2  448.46   405.2  467.82
#Mann= 3 ,-1 , 0
       0     .12       0  200.04    .045       0  216.65     .12       0
Bank Sta=200.04,216.65
XS Rating Curve= 0 ,0
Exp/Cntr=0.3,0.1

Type RM Length L Ch R = 1 ,3604.6  ,225.5,231.9,238.2
XS GIS Cut Line= 2
     2404872.362      325809.376     2404919.578      325424.807
#Sta/Elev= 30
       0  415.36       8  414.24      36  413.95    47.9  414.54    71.9   412.6
   123.8  409.62   135.8  407.84   155.8  403.09   163.8  402.11   183.7  401.25
   215.7  401.72   219.7  401.04  229.12398.1454   235.7  397.28   239.7  397.29
   243.7  397.86   244.7398.4544   247.6  400.17   251.6  404.88   255.6  410.95
   259.6  416.36   263.6  420.57   275.6  431.39   279.6  434.14   327.5  464.57
   339.5   472.7   351.5     480   359.5  482.95   371.5  490.01   387.5  495.96
#Mann= 3 ,-1 , 0
       0     .12       0  229.12    .045       0   244.7     .12       0
Bank Sta=229.12,244.7
XS Rating Curve= 0 ,0
Exp/Cntr=0.3,0.1

Type RM Length L Ch R = 1 ,3372.8  ,237.7,237.5,237.4
XS GIS Cut Line= 3
     2405033.325      325842.607     2405131.383      325613.175
     2405135.075      325481.033
#Sta/Elev= 30
       0  413.27    15.8  410.43    35.6  408.97    51.5  408.46    63.4  407.08
    67.3  407.04    75.2  405.81   138.6  402.86   158.4  401.67   170.3  400.58
     198  400.28     212  396.42   217.8  395.92   221.8  396.17   225.8  396.86
     227  397.34   229.7  398.42   233.7  401.59   237.6  407.37   241.6  412.58
   245.6  416.39   257.3     426   261.2  428.63   272.8  434.39   280.6  439.34
   292.3  446.11   307.8  453.19   323.4  458.72   354.5  471.19   381.7  480.01
#Mann= 3 ,-1 , 0
       0     .12       0     212    .045       0     227     .12       0
Bank Sta=212,227
XS Rating Curve= 0 ,0
Exp/Cntr=0.3,0.1

Type RM Length L Ch R = 1 ,3135.3  ,310.5,309.1,307.6
XS GIS Cut Line= 3
     2405261.982      325903.818     2405351.001        325691.3
     2405438.191      325593.777
#Sta/Elev= 30
       0  407.29       8  406.62    23.8  404.78    59.6  402.91    67.5  402.25
    91.4  401.61   107.3  400.53     139  399.28   154.9  398.88   166.8  399.17
   170.8  398.55   180.2  395.53   182.7  394.81   186.7  394.69   195.2  395.61
   198.6  395.95   202.6  400.16   206.6  405.76   210.6  410.52   214.5  413.97
   218.5  416.86   226.4  423.22   238.3  431.09   246.3  435.53   262.1  441.93
   285.9  449.87   293.8  451.76   305.7  455.29   325.6  460.43   361.2  468.52
#Mann= 3 ,-1 , 0
       0     .12       0   180.2    .045       0   195.2     .12       0
Bank Sta=180.2,195.2
XS Rating Curve= 0 ,0
Exp/Cntr=0.3,0.1

Type RM Length L Ch R = 1 ,2826.2  ,296.5,298.4,300.1
XS GIS Cut Line= 3
     2405557.478      326024.634     2405566.279      325930.016
     2405658.074       325680.61
#Sta/Elev= 30
       0  412.52    43.6   406.8   114.9  399.93   118.8  398.98   126.8  395.25
   135.6  393.34   138.7  392.97   146.6  393.05   150.6  393.35   158.5  395.46
   170.4  395.62   178.3  396.87   182.3  397.17   198.2   397.6     214  396.66
     218  396.86     222  398.16   225.9  401.41   237.8  414.17   245.8   420.7
   253.7  426.26   281.5  442.77   293.4  450.17   297.3  452.85   309.2   459.7
   317.2  464.64   329.1  471.01     341  477.89   344.9  479.74   360.8  486.42
#Mann= 3 ,-1 , 0
       0     .12       0   135.6    .045       0   150.6     .12       0
Bank Sta=135.6,150.6
XS Rating Curve= 0 ,0
Exp/Cntr=0.3,0.1

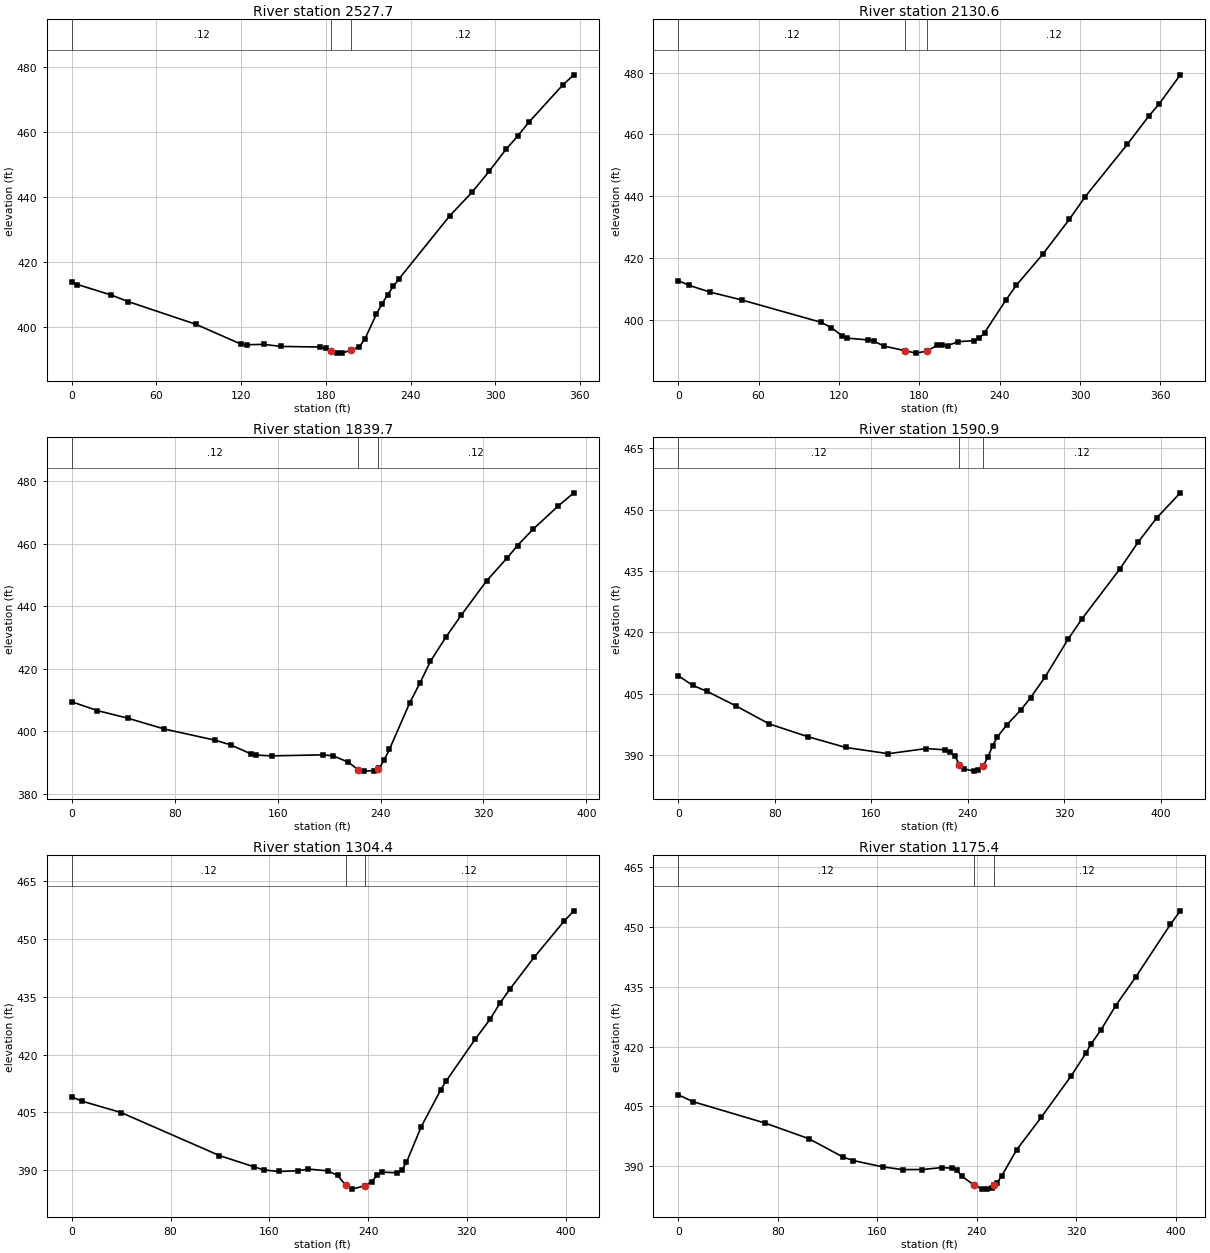
Type RM Length L Ch R = 1 ,2527.7  ,396.8,397.2,398.1
XS GIS Cut Line= 2
     2405786.494      326117.568      2405917.67       325786.91
#Sta/Elev= 30
       0   413.8       4  412.99      28  409.75      40  407.73    87.9  400.76
   119.9  394.65   123.9  394.46   135.9  394.58   147.9  393.95   175.9  393.75
   179.9  393.31   183.9  392.44   187.9  391.88   191.8  391.94  198.01392.8091
   203.8  393.88   207.8  396.34   215.8  403.86   219.8  407.04   223.8  409.87
   227.8  412.39   231.8  414.71   267.8  434.14   283.8  441.48   295.8  447.87
   307.8  454.68   315.8  458.59   323.8  462.91   347.7   474.3   355.7   477.5
#Mann= 3 ,-1 , 0
       0     .12       0   183.9    .045       0  198.01     .12       0
Bank Sta=183.9,198.01
XS Rating Curve= 0 ,0
Exp/Cntr=0.3,0.1

Type RM Length L Ch R = 1 ,2130.6  ,287.4,290.9,292
XS GIS Cut Line= 3
     2406111.675      326276.583     2406168.375      326120.929
     2406247.031      325927.081
#Sta/Elev= 30
       0  412.88     7.9  411.35    23.7  409.15    47.3  406.62   106.5  399.42
   114.4  397.66   122.3  395.05   126.2  394.29     142  393.71   145.9  393.34
   153.8   391.7   169.6  390.22   177.5  389.45   185.4  390.08   193.3  391.93
   197.2   392.2   201.2   391.9   209.1  393.15   220.9  393.48   224.9  394.23
   228.8  396.08   244.6  406.53   252.5  411.38   272.2  421.36     292  432.59
   303.8  439.88   335.4  456.86   351.2  465.84   359.1  469.85   374.9  479.25
#Mann= 3 ,-1 , 0
       0     .12       0   169.6    .045       0   185.4     .12       0
Bank Sta=169.6,185.4
XS Rating Curve= 0 ,0
Exp/Cntr=0.3,0.1

Type RM Length L Ch R = 1 ,1839.7  ,241.7,248.8,252.1
XS GIS Cut Line= 2
     2406327.573      326391.279     2406512.328      326047.512
#Sta/Elev= 30
       0  409.48    19.9  406.66    43.8  404.21    71.7   400.8   111.5  397.19
   123.4  395.72   139.4  392.81   143.4  392.44   155.3  392.19   195.1  392.51
   203.1  392.22     215  390.16   222.8  387.69     227  387.31     235  387.49
   237.8     388   238.9   388.2   242.9  390.89   246.9  394.23   262.8   409.2
   270.8   415.6   278.8  422.41   290.7  430.07   302.7  437.13   322.6  448.21
   338.5  455.48   346.5  459.44   358.4  464.57   378.3  472.13   390.3  476.28
#Mann= 3 ,-1 , 0
       0     .12       0   222.8    .045       0   237.8     .12       0
Bank Sta=222.8,237.8
XS Rating Curve= 0 ,0
Exp/Cntr=0.3,0.1

Type RM Length L Ch R = 1 ,1590.9  ,285.5,286.6,288.4
XS GIS Cut Line= 4
     2406456.496      326495.247     2406545.446      326435.224
     2406665.097      326269.483     2406676.791      326165.698
#Sta/Elev= 30
       0  409.43    11.9  407.08    23.8  405.61    47.7  402.07    75.5  397.63
   107.3  394.53   138.8  391.89   174.1  390.36   205.6  391.62   221.3   391.3
   225.2  390.77   229.2  389.86   233.1  387.68     237  386.67   244.9   386.1
   248.8  386.33   252.8  387.34   256.7  389.52   260.6  392.26   264.6  394.49
   272.4  397.43   284.2  401.11   292.1  404.08   303.9  409.02   323.3   418.4
   334.9   423.4   365.9  435.44   381.4  442.14   396.8  448.06   416.2  454.13
#Mann= 3 ,-1 , 0
       0     .12       0   233.1    .045       0   252.8     .12       0
Bank Sta=233.1,252.8
XS Rating Curve= 0 ,0
Exp/Cntr=0.3,0.1

Type RM Length L Ch R = 1 ,1304.4  ,134.6,128.9,124.4
XS GIS Cut Line= 2
      2406638.26      326694.773     2406935.964      326417.665
#Sta/Elev= 30
       0     409       8  407.94    39.9  404.97   119.6  393.81   147.5   390.9
   155.5  390.09   167.5  389.68   183.4  389.86   191.4  390.31   207.3  389.84
   215.3  388.66  222.07386.0417   227.3   385.1  237.14385.9724   243.2  387.06
   247.2  388.69   251.2   389.5   263.2  389.35   267.2  389.98   271.1  392.04
   283.1   401.3     299  410.92     303  413.02     327  424.09   338.9  429.18
   346.9  433.37   354.9  436.98   374.8  445.33   398.7  454.56   406.7  457.28
#Mann= 3 ,-1 , 0
       0     .12       0  222.07    .045       0  237.14     .12       0
Bank Sta=222.07,237.14
XS Rating Curve= 0 ,0
Exp/Cntr=0.3,0.1

Type RM Length L Ch R = 1 ,1175.4  ,147.4,178.3,203.6
XS GIS Cut Line= 3
     2406730.468      326781.858     2406831.904      326724.286
     2406983.573       326480.61
#Sta/Elev= 30
       0  407.93    11.7  406.21      70   400.8     105   396.9   132.6  392.28
   140.6  391.42   164.5  389.82   180.4  389.14   196.4  389.16   212.3  389.66
   220.3  389.47   224.3  388.92   228.3  387.42  237.98385.2062   244.2  384.34
   248.2  384.24   252.2  384.58  254.19 385.177   256.2  385.78   260.2  387.61
   272.1  394.11     292  402.32     316  412.68   327.9  418.42   331.9  420.64
   339.9   424.2   351.8  430.32   367.8  437.45   395.7  450.66   403.7  454.09
#Mann= 3 ,-1 , 0
       0     .12       0  237.98    .045       0  254.19     .12       0
Bank Sta=237.98,254.19
XS Rating Curve= 0 ,0
Exp/Cntr=0.3,0.1

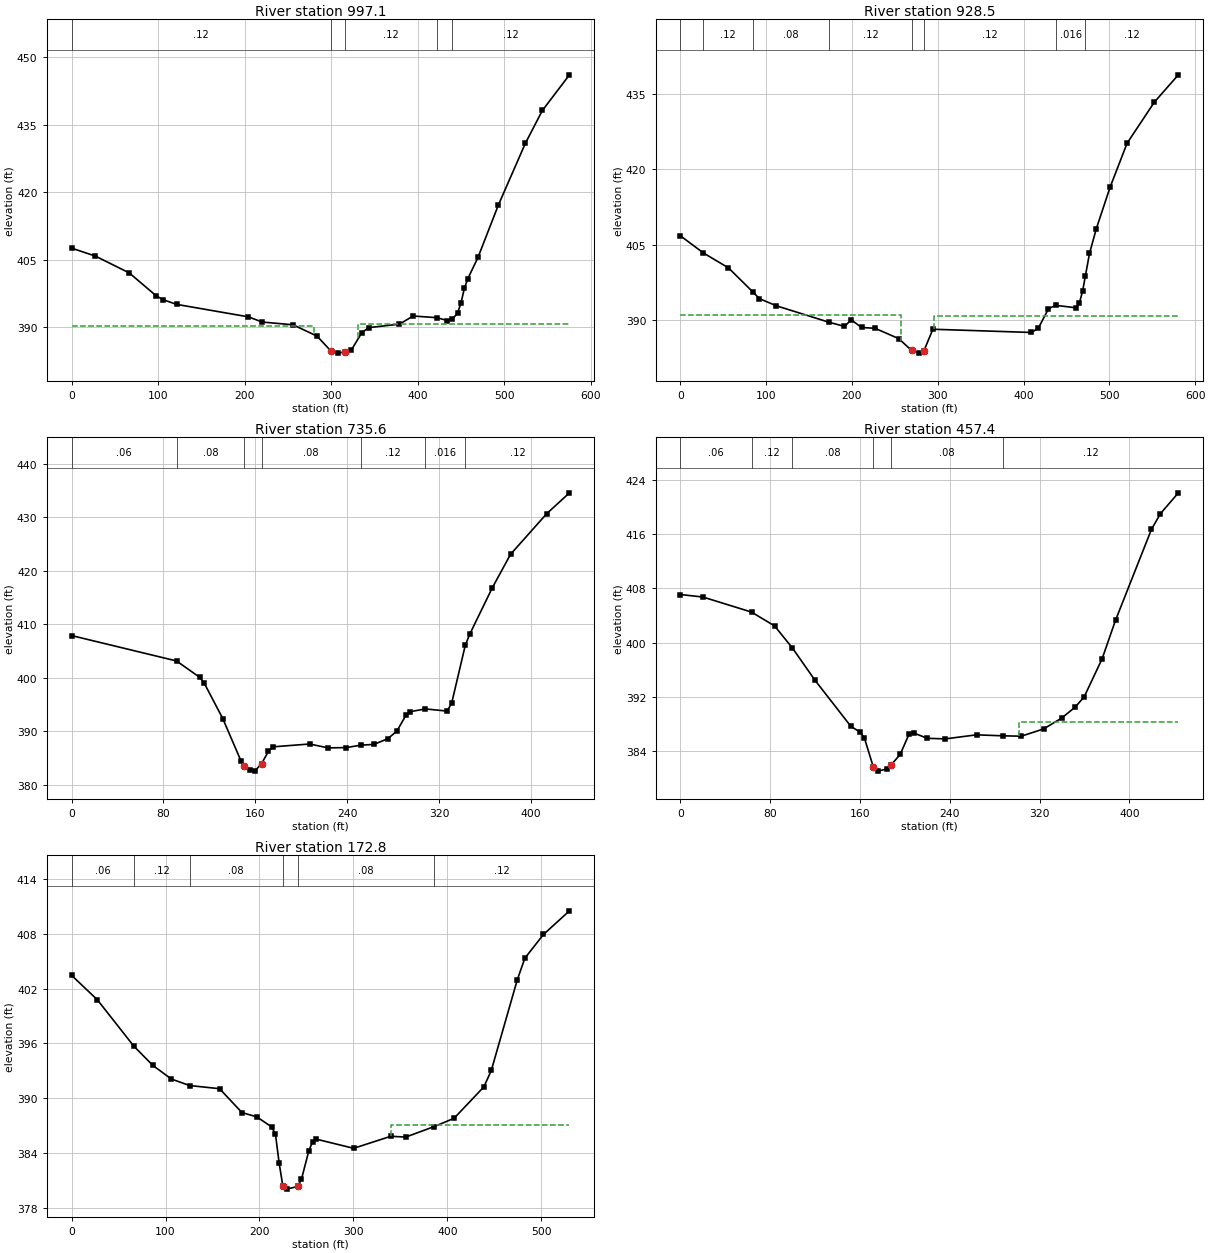
Type RM Length L Ch R = 1 ,997.1   ,75.5,68.6,65.7
XS GIS Cut Line= 4
     2406742.503      326793.224     2406877.043      326729.495
     2407166.106      326719.946     2407186.802      326584.533
#Sta/Elev= 30
       0  407.58    27.4  405.82    66.6  402.08    97.9  396.97   105.8  396.13
   121.4  395.09   204.3  392.32   220.2  391.17   255.8  390.56   283.6  388.04
   299.4  384.77   307.4  384.27   315.3  384.52   323.2  384.97   335.1  388.76
     343  389.93   378.7   390.7   394.5  392.51  421.65392.1427   434.1  391.51
  439.85391.7931   445.9  393.19   449.8  395.43   453.8  398.72   457.7   400.8
   469.4  405.51   492.9  417.11   524.2  430.87   543.8  438.14   575.1  446.05
#Mann= 5 ,-1 , 0
       0     .12       0   299.4    .045       0   315.3     .12       0
  421.65    .016       0  439.85     .12       0
#XS Ineff= 2 , 0
          279.88  390.29  331.27          390.64
Permanent Ineff=
       F       F
Bank Sta=299.4,315.3
XS Rating Curve= 0 ,0
Exp/Cntr=0.3,0.1

Type RM Length L Ch R = 1 ,928.5   ,224.1,192.8,163.1
XS GIS Cut Line= 4
      2406850.76      326877.489     2406923.918      326782.446
     2407212.981      326772.898     2407238.183       326603.41
#Sta/Elev= 30
       0  406.76   26.83403.3504      56   400.4   84.75395.5681      92   394.3
   111.9  392.87  173.53389.5914   191.2  388.79   199.2  390.08   211.1  388.57
   226.9  388.41   254.6  386.35  269.51384.0034   278.4  383.48  283.97383.9789
   294.3  388.22   409.2  387.58   417.1  388.39   429.1  392.29  437.36392.9691
     461  392.48     465  393.34   468.9  395.82  472.16398.8518   476.9  403.26
   484.9   408.2   500.8  416.36   520.7  425.13   552.6  433.31   580.5  438.71
#Mann= 8 ,-1 , 0
       0     .06       0   26.83     .12       0   84.75     .08       0
  173.53     .12       0  269.51    .045       0  283.97     .12       0
  437.36    .016       0  472.16     .12       0
#XS Ineff= 2 , 0
          256.97  390.95  295.98          390.84
Permanent Ineff=
       F       F
Bank Sta=269.51,283.97
XS Rating Curve= 0 ,0
Exp/Cntr=0.3,0.1

Type RM Length L Ch R = 1 ,735.6   ,275.4,278.2,280.3
XS GIS Cut Line= 3
     2407186.071      327037.655      2407262.46      326732.099
     2407277.887      326614.616
#Sta/Elev= 30
       0  407.88   91.35403.1345   111.6  400.07   115.6  398.94   131.6  392.38
   147.5  384.44   150.4  383.56   155.5  382.69   159.5  382.55   165.4  383.96
   171.4  386.26   175.4  387.09   207.3  387.62   223.3  386.89   239.2  386.95
  251.67387.4012   263.1  387.54   275.1  388.59   283.1  390.01     291  392.97
     295  393.67  308.04394.1714   326.8  393.77   330.8   395.2  342.69406.0582
   346.6  408.15   366.3  416.84   382.1  423.06   413.7  430.68   433.4  434.55
#Mann= 7 ,-1 , 0
       0     .06       0   91.35     .08       0   150.4    .045       0
   165.4     .08       0  251.67     .12       0  308.04    .016       0
  342.69     .12       0
Bank Sta=150.4,165.4
XS Rating Curve= 0 ,0
Exp/Cntr=0.3,0.1

Type RM Length L Ch R = 1 ,457.4   ,284.5,284.6,284.5
XS GIS Cut Line= 2
     2407416.362      327112.391     2407566.809      326695.079
#Sta/Elev= 30
       0   407.1      20  406.73   63.31404.5145    83.9  402.47   99.66 399.238
   119.9  394.46   151.9  387.66   159.9  386.84   163.8     386   171.8   381.7
   175.8  381.07   183.8  381.38   187.8     382   195.8  383.54   203.8  386.58
   207.8   386.7   219.8  385.91   235.8  385.82   263.8  386.42  287.26386.2732
   303.7  386.22   323.7   387.3   339.7   388.9   351.7  390.51   359.7  392.02
   375.7  397.64   387.6   403.3   419.6  416.69   427.6  419.01   443.6  422.09
#Mann= 6 ,-1 , 0
       0     .06       0   63.31     .12       0   99.66     .08       0
   171.8    .045       0   187.8     .08       0  287.26     .12       0
#XS Ineff= 2 , 0
                          301.86          388.36
Permanent Ineff=
       F       F
Bank Sta=171.8,187.8
XS Rating Curve= 0 ,0
Exp/Cntr=0.3,0.1

Type RM Length L Ch R = 1 ,172.8   ,166.9,172.8,177.5
XS GIS Cut Line= 3
     2407563.885      327154.459     2407696.347      327135.802
     2407817.817       326758.74
#Sta/Elev= 30
       0  403.46    27.5  400.77    66.1395.7184    86.6  393.58   106.2   392.1
  125.58391.3857   157.5  391.04   181.3  388.43   197.2  387.95     213  386.85
     217  386.04   220.9  382.91   224.9  380.34   228.8  380.04   240.7380.3302
   244.7  381.14   252.6  384.27   256.6  385.24   260.5  385.51   300.2  384.51
   339.8  385.83   355.6  385.74   386.1 386.898   407.1   387.8   438.8  391.24
   446.7  393.04   474.4  402.98   482.4  405.33   502.2  407.93   529.9  410.52
#Mann= 6 ,-1 , 0
       0     .06       0    66.1     .12       0  125.58     .08       0
   224.9    .045       0   240.7     .08       0   386.1     .12       0
#XS Ineff= 2 , 0
                          339.94          387.09
Permanent Ineff=
       F       F
Bank Sta=224.9,240.7
XS Rating Curve= 0 ,0
Exp/Cntr=0.3,0.1

Chan Stop Cuts=-1
Use User Specified Reach Order=0
Composite Channel Slope=5